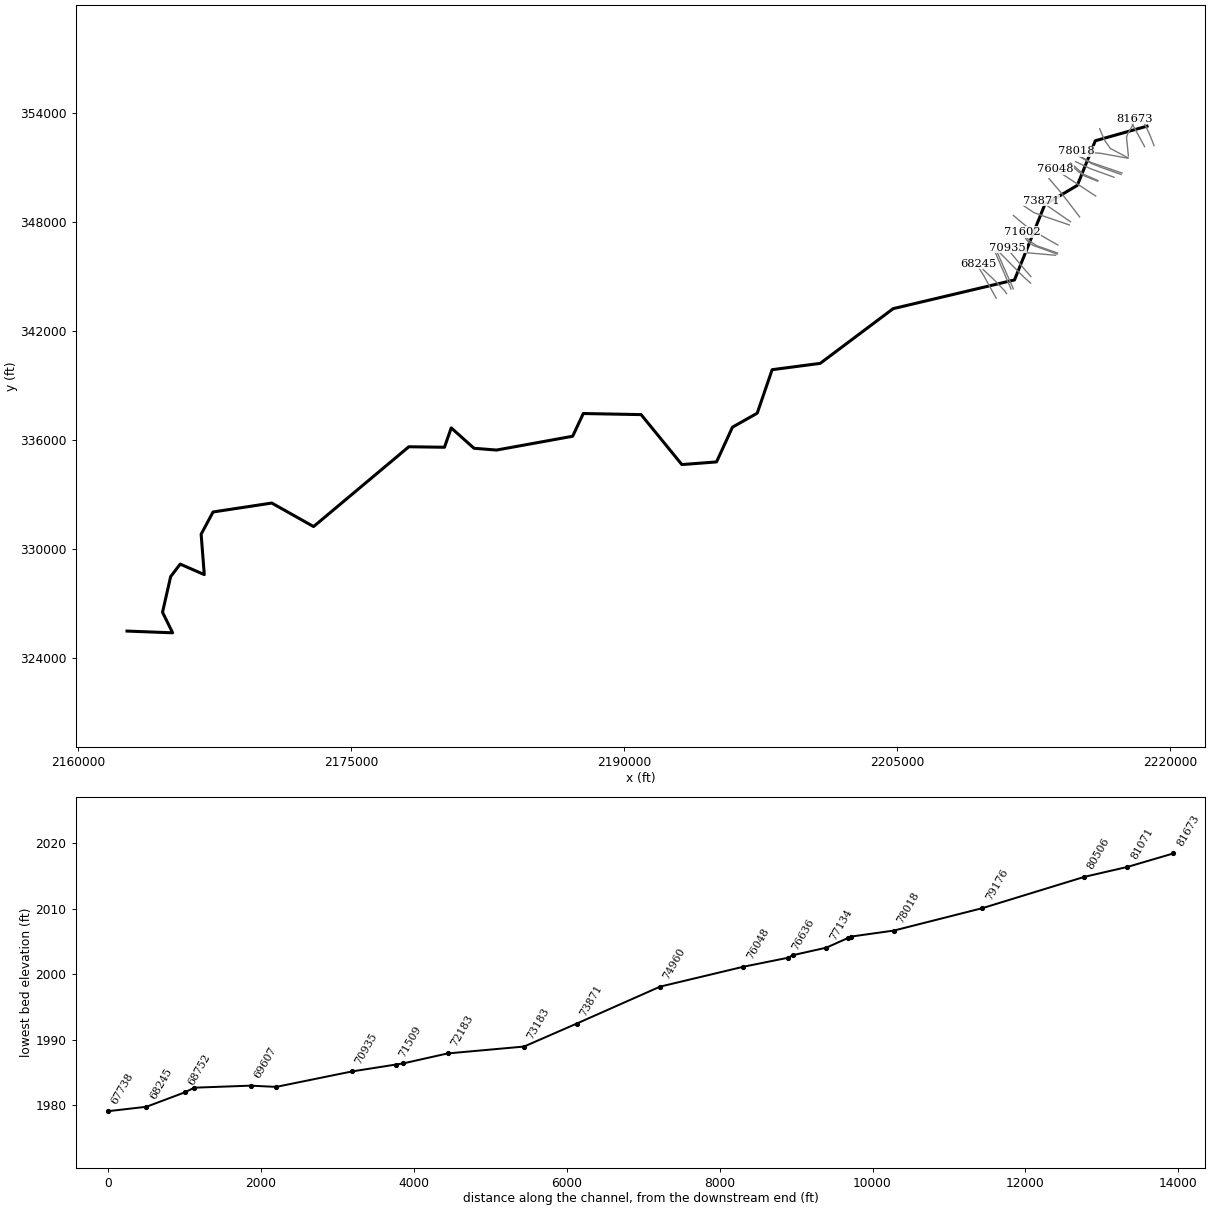
--- ANTHONYCK.prj (project) ---

Proj Title=ANTHONYCK
Current Plan=p01
Default Exp/Contr=0.3,0.1
English Units
Geom File=g01
Flow File=f01
Plan File=p01
Y Axis Title=Elevation
X Axis Title(PF)=Main Channel Distance
X Axis Title(XS)=Station
BEGIN DESCRIPTION:
Stream Name- Anthony Creek
Flood Zone: Zone A
Greenbrier County, WV
County-Wide Study
WVDHSEM-2018-3, Flood Risk Project
HEC-RAS Version: 5.0.7
General Notes:
For the Hydrology Regression was used.
END DESCRIPTION:
DSS File=dss
DSS Export Rating Curves= 0
DSS Export Rating Curve Sorted= 0
DSS Export Volume Flow Curves= 0
DXF OffsetX= 0
DXF OffsetY= 0
DXF ScaleX= 1
DXF ScaleY= 10

--- ANTHONYCK.p01 (plan) ---

Plan Title=Floodplain
Program Version=5.07
Short Identifier=Floodplain
Geom File=g01
Flow File=f01
Subcritical Flow
K Sum by GR= 0
Std Step Tol= 0.01
Critical Tol= 0.01
Num of Std Step Trials= 20
Max Error Tol= 0.3
Flow Tol Ratio= 0.001
Split Flow NTrial= 30
Split Flow Tol= 0.02
Split Flow Ratio= 0.02
Log Output Level= 0
Friction Slope Method= 1
Unsteady Friction Slope Method= 2
Unsteady Bridges Friction Slope Method= 1
Parabolic Critical Depth
Global Vel Dist= 0 , 0 , 0
Global Log Level= 0
CheckData=True
Encroach Param=-1 ,0,0, 0
Computation Interval=1MIN
Output Interval=1HOUR
Instantaneous Interval=1HOUR
Mapping Interval=1HOUR
Computation Time Step Use Courant=        0
Computation Time Step Use Time Series=    0
Computation Time Step Count To Double=0
Computation Time Step Max Doubling=0
Computation Time Step Max Halving=0
Computation Time Step Residence Courant=0
Run HTab= 0
Run UNet= 0
Run Sediment= 0
Run PostProcess= 0
Run WQNet= 0
Run RASMapper= 0
UNET Theta= 1
UNET Theta Warmup= 1
UNET ZTol= 0.02
UNET ZSATol= 0.02
UNET MxIter= 20
UNET Max Iter WO Improvement= 0
UNET MaxInSteps= 0
UNET DtIC= 0
UNET DtMin= 0
UNET MaxCRTS= 20
UNET WFStab= 2
UNET SFStab= 1
UNET WFX= 1
UNET SFX= 1
UNET 1D Methodology=Finite Difference
UNET DSS MLevel= 4
UNET Pardiso=0
UNET DZMax Abort= 100
UNET Use Existing IB Tables=-1
UNET Froude Reduction=False
UNET Froude Limit= 0.8
UNET Froude Power= 4
UNET D1 Cores= 0
UNET D2 Coriolis=0
UNET D2 Cores= 0
UNET D2 Theta= 1
UNET D2 Theta Warmup= 1
UNET D2 Z Tol= 0.01
UNET D2 Volume Tol= 0.01
UNET D2 Max Iterations= 20
UNET D2 Equation= 0
UNET D2 RampUpFraction=0.1
UNET D2 TimeSlices= 1
UNET D2 BCVolumeCheck=0
UNET D1D2 MaxIter= 0
UNET D1D2 ZTol=0.01
UNET D1D2 QTol=0.1
UNET D1D2 MinQTol=1
DSS File=dss
Write IC File= 0
Write IC File at Fixed DateTime=0
Write IC File at Sim End=0
Echo Input=False
Echo Parameters=False
Echo Output=False
Write Detailed= 0
HDF Write Warmup=0
HDF Write Time Slices=0
HDF Flush=0
HDF Face Node Velocities=0
HDF Compression= 1
HDF Chunk Size= 1
HDF Spatial Parts= 1
HDF Use Max Rows=0
HDF Fixed Rows= 1
Calibration Method= 0
Calibration Iterations= 20
Calibration Max Change=0.05
Calibration Tolerance=0.2
Calibration Maximum=1.5
Calibration Minimum=0.5
Calibration Optimization Method= 1
WQ AD Non Conservative
WQ ULTIMATE=-1
WQ Max Comp Step=1HOUR
WQ Output Interval=15MIN
WQ Output Selected Increments= 0
WQ Output face flow=0
WQ Output face velocity=0
WQ Output face area=0
WQ Output face dispersion=0
WQ Output cell volume=0
WQ Output cell surface area=0
WQ Output cell continuity=0
WQ Output cumulative cell continuity=0
WQ Output face conc=0
WQ Output face dconc_dx=0
WQ Output face courant=0
WQ Output face peclet=0
WQ Output face adv mass=0
WQ Output face disp mass=0
WQ Output cell mass=0
WQ Output cell source sink temp=0
WQ Output nsm pathways=0
WQ Output nsm derived pathways=0
WQ Output MaxMinRange=-1
WQ Daily Max Min Mean=-1
WQ Daily Range=0
WQ Daily Time=0
WQ Create Restart=0
WQ Fixed Restart=0
WQ System Summary=0
WQ Write To DSS=0
WQ Use Fixed Temperature=0
Sorting and Armoring Iterations= 10
XS Update Threshold= 0.02
Bed Roughness Predictor= 0
Hydraulics Update Threshold= 0.02
Energy Slope Method= 1
Volume Change Method= 1
Sediment Retention Method= 0
XS Weighting Method= 0
Number of US Weighted Cross Sections= 1
Number of DS Weighted Cross Sections= 1
Upstream XS Weight=0
Main XS Weight=1
Downstream XS Weight=0
Number of DS XS's Weighted with US Boundary= 1
Upstream Boundary Weight= 1
Weight of XSs Associated with US Boundary= 0
Number of US XS's Weighted with DS Boundary= 1
Downstream Boundary Weight= 0.5
Weight of XSs Associated with DS Boundary= 0.5
Percentile Method= 0
Sediment Output Level= 3
Mass or Volume Output= 0
Output Increment Type= 1
Profile and TS Output Increment= 1
XS Output Flag= 0
XS Output Increment= 10
Write Gradation File= 0
Read Gradation Hotstart= 0
Write HDF5 File= 1
Write Binary Output= 1
Write DSS Sediment File= 0
SV Curve= 0
Specific Gage Flag= 0

--- ANTHONYCK.f01 (steady flow) ---

Flow Title=Flow
Program Version=5.07
Number of Profiles= 6
Profile Names=f1p,f10p,f4p,f2p,f02p,f1pplus
River Rch & RM=ANTHONYCK,Main            ,81673
   16700   10100   12500   14500   22700   19200
River Rch & RM=ANTHONYCK,Main            ,70935
   18700   11300   14000   16200   25300   21400
River Rch & RM=ANTHONYCK,Main            ,47360
   20800   12600   15700   18100   28100   23800
River Rch & RM=ANTHONYCK,Main            ,37120
   24400   14800   18400   21300   32800   28000
Boundary for River Rch & Prof#=ANTHONYCK,Main            , 1
Up Type= 0
Dn Type= 3
Dn Slope=0.00591
Boundary for River Rch & Prof#=ANTHONYCK,Main            , 2
Up Type= 0
Dn Type= 3
Dn Slope=0.00591
Boundary for River Rch & Prof#=ANTHONYCK,Main            , 3
Up Type= 0
Dn Type= 3
Dn Slope=0.00591
Boundary for River Rch & Prof#=ANTHONYCK,Main            , 4
Up Type= 0
Dn Type= 3
Dn Slope=0.00591
Boundary for River Rch & Prof#=ANTHONYCK,Main            , 5
Up Type= 0
Dn Type= 3
Dn Slope=0.00591
Boundary for River Rch & Prof#=ANTHONYCK,Main            , 6
Up Type= 0
Dn Type= 3
Dn Slope=0.00591
DSS Import GetInterval= 0
DSS Import GetPeak= 0
DSS Import FillOption= 0

--- ANTHONYCK.g01 (geometry) ---

Geom Title=Geometry
Program Version=5.07

River Reach=ANTHONYCK       ,Main
Reach XY= 30
 2218729.1953263353260.7115202252215888.64720164352458.013322473
2214899.75843139350004.8883074822213110.86962073348943.777240723
2211448.28862831344805.537485734 2204780.3137753343224.795568481
2200770.59180789340216.4623463152198128.92517522339868.545719311
2197308.92451863337475.563956723 2195948.9771073336706.740035057
 2195072.9355523334796.3232522312193167.72709239334650.490210563
2190928.86608456337397.660569221 2187751.0604323337457.781840056
2187166.68528873336207.7817153932182982.31045538335448.406593725
2181744.81030571 335547.365057232180493.76884456336667.156780899
2180122.08946981335602.4568105642178163.75578806335630.234970227
2172929.38043006331241.3454540672170631.37912056332534.101398721
2167405.07454956332043.4298078862166750.01877305330821.323328227
2166922.43575105 328598.985253232165597.93544731329176.531670317
2165073.29476431328485.5714380592164627.51481597326530.237422228
2165182.85261606325397.5959867242162676.54496464325493.457999721

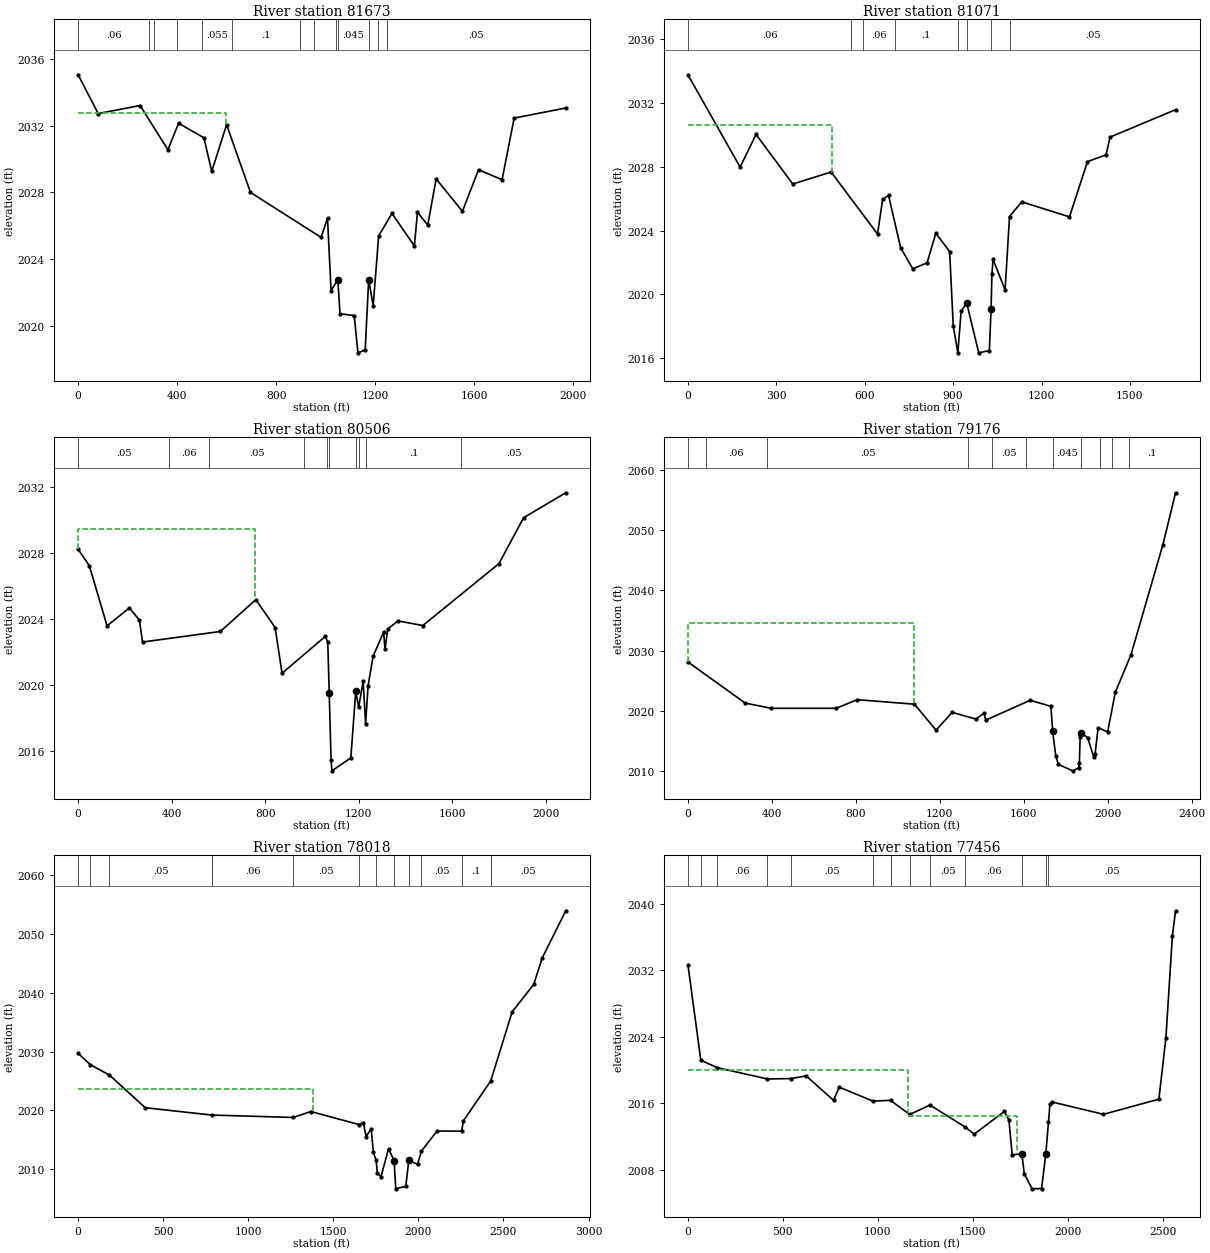
Type RM Length L Ch R = 1 ,81673   ,600.1,601.3,601.3
XS GIS Cut Line= 4
 2219117.8756513352191.1057198052218878.69043414352794.449001312
2218537.40305898353529.0288969732218044.05726089353660.998121232
#Sta/Elev= 30
       0 2035.04      81 2032.72   250.4  2033.2   362.8 2030.55   405.7 2032.14
     508 2031.27   539.8 2029.26   599.8 2032.05   696.2    2028   981.5 2025.31
  1007.4 2026.46  1021.8 2022.12  1049.1 2022.78    1058 2020.74  1115.2 2020.63
  1130.4  2018.4  1159.7 2018.58 1173.712022.775  1191.9 2021.22  1214.1  2025.4
  1267.8 2026.74  1358.3  2024.8  1370.8 2026.81  1412.5 2026.05  1446.2 2028.81
  1552.3 2026.87  1617.5 2029.36  1712.6 2028.76  1761.3 2032.45  1969.7 2033.05
#Mann= 13 ,-1 , 0
       0     .06       0  285.92      .1       0  305.27     .06       0
  399.07      .1       0  499.03    .055       0  621.44      .1       0
  896.91      .1       0  953.16      .1       0 1043.02      .1       0
  1049.1    .045       0 1173.71      .1       0 1211.03      .1       0
 1247.06     .05       0
#XS Ineff= 2 , 0
          596.49 2032.74
Permanent Ineff=
       F       F
Bank Sta=1049.1,1173.71
XS Rating Curve= 0 ,0
Exp/Cntr=0.3,0.1

Type RM Length L Ch R = 1 ,81071   ,618.2,565.2,528.6
XS GIS Cut Line= 3
2218599.34847313 352133.665545972217967.69586505353299.266233146
2217928.30355538353625.925028637
#Sta/Elev= 30
       0 2033.78   177.1 2027.99   231.1 2030.04   355.8 2026.93   485.9 2027.68
   643.5 2023.79   660.7 2025.96   680.9 2026.21   721.9 2022.93     763 2021.61
   811.5 2021.98   841.3 2023.84   888.2 2022.69   900.3 2018.05     916 2016.34
   927.1 2018.95  946.032019.465   986.9 2016.34    1023 2016.48 1028.862019.111
  1031.6 2021.26  1035.4  2022.2  1076.4 2020.29  1091.3 2024.89  1132.7 2025.81
  1294.8 2024.87  1355.9 2028.33  1418.9 2028.76  1432.5 2029.87  1654.8 2031.59
#Mann= 8 ,-1 , 0
       0     .06       0   554.5     .05       0  595.11     .06       0
  701.98      .1       0  915.02      .1       0  946.03    .045       0
 1028.86      .1       0 1094.39     .05       0
#XS Ineff= 2 , 0
          489.98 2030.63
Permanent Ineff=
       F       F
Bank Sta=946.03,1028.86
XS Rating Curve= 0 ,0
Exp/Cntr=0.3,0.1

Type RM Length L Ch R = 1 ,80506   ,1266.5,1330.1,1361.7
XS GIS Cut Line= 6
2217707.68194939351614.9155992272217603.13819522352660.217642471
2217690.63834831352885.2175205652217912.86067289353258.828649983
 2217931.7756613353325.5778603112217903.99782972353613.772165805
#Sta/Elev= 30
       0 2028.24    48.1 2027.24   123.9  2023.6   219.5 2024.69   262.4 2023.94
   275.6 2022.62   608.6 2023.26   760.2 2025.19   842.7  2023.5   872.4 2020.73
  1057.4 2022.96    1068 2022.62 1074.192019.524  1082.1 2015.47  1085.6 2014.82
  1166.6  2015.6 1187.542019.627  1200.2 2018.69  1219.4 2020.24  1229.9 2017.68
  1240.5 2019.97  1261.6 2021.75  1306.8 2023.22  1312.9 2022.19  1324.5 2023.41
  1368.1  2023.9  1474.6 2023.62  1800.3 2027.37  1905.7 2030.15  2085.9 2031.66
#Mann= 10 ,-1 , 0
       0     .05       0  387.46     .06       0  561.45     .05       0
   966.2    .055       0 1066.81      .1       0 1074.19    .045       0
 1187.54      .1       0 1202.33      .1       0 1233.36      .1       0
 1638.97     .05       0
#XS Ineff= 2 , 0
          756.93 2029.44
Permanent Ineff=
       F       F
Bank Sta=1074.19,1187.54
XS Rating Curve= 0 ,0
Exp/Cntr=0.3,0.1

Type RM Length L Ch R = 1 ,79176   ,1072.4,1157.9,1206.9
XS GIS Cut Line= 5
2217673.09868522351527.5545534792216715.85322438352033.872110397
2216394.80498198352492.1618762312216265.63824555352792.161932394
 2216129.5272973353118.551043391
#Sta/Elev= 30
       0 2028.13   272.9  2021.3   396.7 2020.44   706.1 2020.44   806.3 2021.87
  1078.9 2021.12    1182 2016.81  1258.7 2019.76  1370.8 2018.66  1410.9 2019.62
  1418.2 2018.47  1630.2 2021.77  1728.9 2020.77 1737.182016.711  1751.8 2012.58
  1764.6 2011.13  1832.4 2010.06  1861.7 2010.56  1864.6 2011.41  1868.2  2015.6
 1871.092016.362  1903.9 2015.57  1932.5 2012.42  1939.6 2012.88  1953.9 2017.24
  1999.2  2016.5  2035.7 2023.09  2110.4 2029.33  2262.6 2047.61  2322.7 2056.21
#Mann= 11 ,-1 , 0
       0     .05       0   84.67     .06       0  375.17     .05       0
 1336.19     .06       0 1447.93     .05       0 1611.64      .1       0
 1737.18    .045       0 1871.09      .1       0 1961.73      .1       0
  2018.3     .05       0 2101.16      .1       0
#XS Ineff= 2 , 0
         1076.68 2034.62
Permanent Ineff=
       F       F
Bank Sta=1737.18,1871.09
XS Rating Curve= 0 ,0
Exp/Cntr=0.3,0.1

Type RM Length L Ch R = 1 ,78018   ,578.5,561.8,535.5
XS GIS Cut Line= 5
2217689.76531856351496.9988403172216156.90683572351772.926766142
 2215875.3604828351793.5510687232215275.17284654351810.763878147
2214855.66349566351882.986101985
#Sta/Elev= 30
       0 2029.71    71.1 2027.79   184.4    2026   394.4 2020.45   784.4  2019.2
  1264.5 2018.79  1367.8  2019.8  1649.9 2017.59  1676.2 2017.91  1692.7 2015.54
  1722.3 2016.86  1735.5 2012.86  1751.6 2011.51  1758.5 2009.29    1780  2008.7
  1824.3 2013.45  1857.1 2011.45    1867 2006.64  1926.1 2007.09  1943.2 2011.48
    1995 2010.81    2018 2013.07  2109.9 2016.48  2254.3 2016.46  2264.1  2018.2
    2425    2025  2551.2 2036.78  2677.7 2041.43  2727.7 2045.94  2865.9 2053.97
#Mann= 12 ,-1 , 0
       0     .05       0    71.1     .06       0   184.4     .05       0
   784.4     .06       0  1264.5     .05       0  1649.9     .06       0
  1751.6      .1       0  1857.1    .045       0  1943.2      .1       0
    2018     .05       0  2254.3      .1       0    2425     .05       0
#XS Ineff= 2 , 0
         1378.61 2023.67
Permanent Ineff=
       F       F
Bank Sta=1857.1,1943.2
XS Rating Curve= 0 ,0
Exp/Cntr=0.5,0.3

Type RM Length L Ch R = 1 ,77456   ,47.9,38,39.2
XS GIS Cut Line= 5
2217359.20954922350683.1100481452216118.24155872351107.426784813
2215658.47673023351260.742423058 2215588.1642068351298.936572388
2214990.60995571351645.232795805
#Sta/Elev= 30
       0 2032.68    67.8  2021.2   154.5  2020.3     418 2018.94     543 2018.99
   622.6 2019.31   766.5 2016.37   796.2 2017.96   974.5 2016.27  1066.4 2016.37
    1167 2014.67  1274.2  2015.8  1458.2 2013.17  1507.5 2012.31  1665.4 2015.03
  1689.6 2014.03  1706.9 2009.81    1758 2009.93  1770.5 2007.54  1811.8 2005.72
  1861.6 2005.76  1883.9 2009.92    1898 2013.75  1905.5 2015.94  1916.9 2016.17
  2187.4 2014.69  2479.1 2016.51  2516.1  2023.9  2550.2 2036.19  2566.8 2039.18
#Mann= 13 ,-1 , 0
       0      .1       0    67.8     .12       0   154.5     .06       0
     418      .1       0     543     .05       0   974.5    .055       0
  1066.4     .06       0    1167    .055       0  1274.2     .05       0
  1458.2     .06       0    1758    .045       0  1883.9      .1       0
    1898     .05       0
#XS Ineff= 3 ,-1
       0    1160    2020    1160    1733  2014.5    1906    2700  2014.5
Permanent Ineff=
       F       F       F
Bank Sta=1758,1883.9
XS Rating Curve= 0 ,0
Exp/Cntr=0.5,0.3

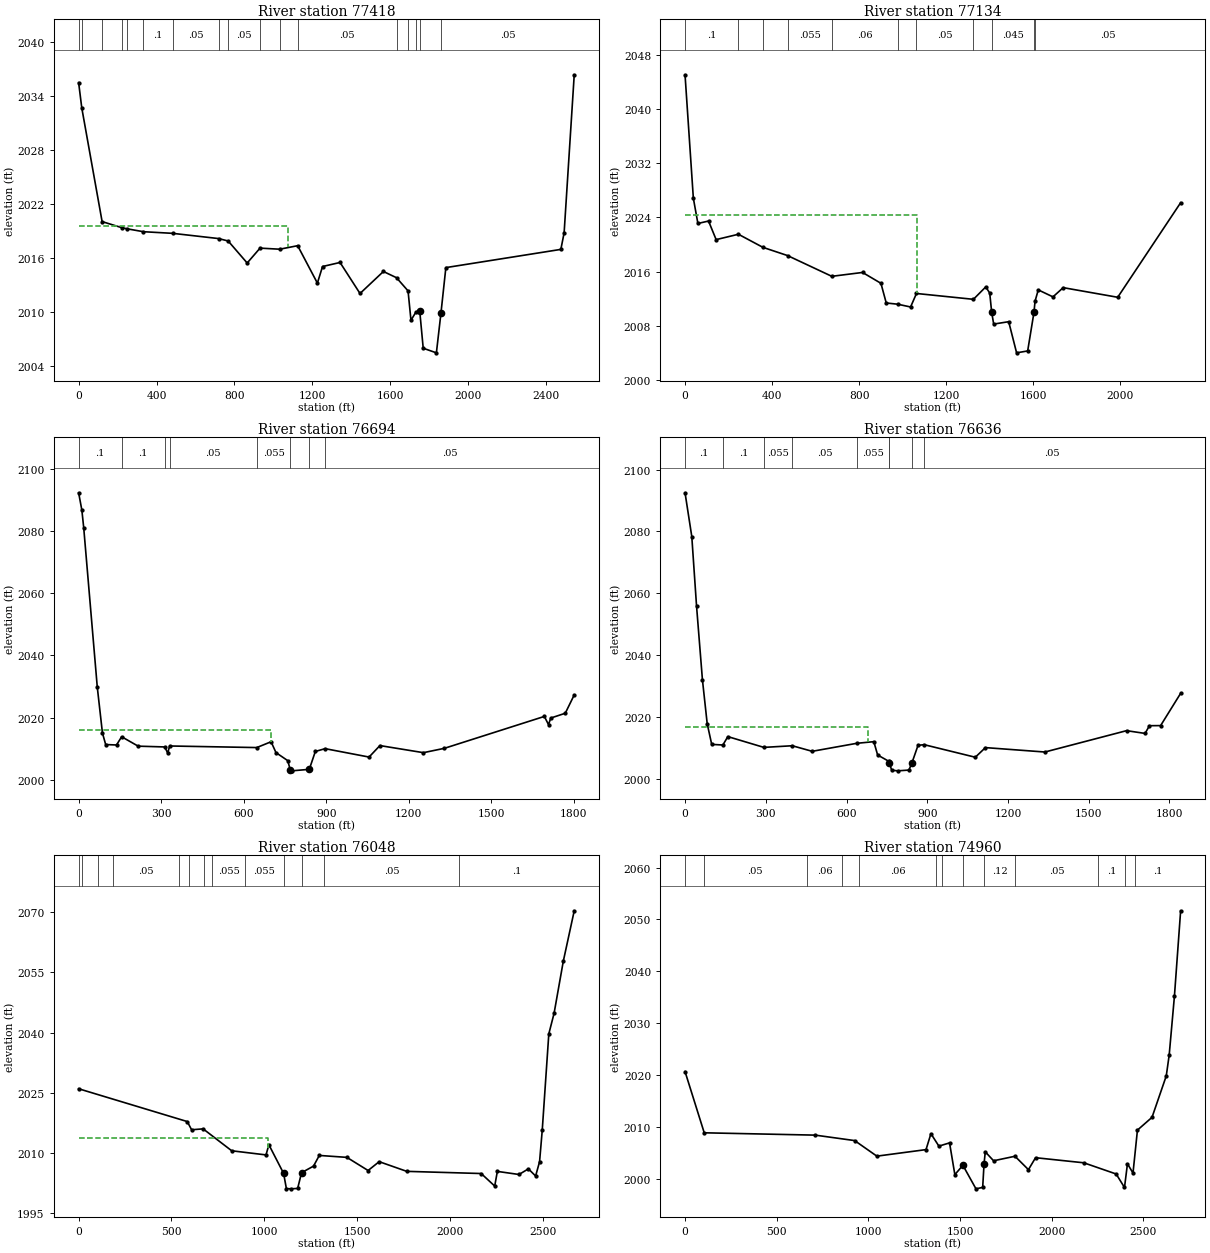
Type RM Length L Ch R = 1 ,77418   ,289,284.6,288.2
XS GIS Cut Line= 5
2217303.65421414350605.3323165632216249.43289739350979.524153471
2215668.02526756351213.5778192282215574.27545506351262.188942477
2214976.72120397351615.719075307
#Sta/Elev= 30
       0 2035.47    16.1 2032.67   120.6 2020.06   221.5 2019.39   246.5 2019.27
   332.9 2018.94   482.6 2018.76   718.9 2018.18     768 2017.91   865.6 2015.47
   931.7 2017.12  1032.7    2017  1124.9 2017.39  1226.2 2013.24  1252.6 2015.08
  1342.5 2015.53  1445.1 2012.09  1565.3 2014.53  1632.5 2013.84  1691.8 2012.38
  1706.8 2009.12  1732.8 2010.05 1751.81 2010.15  1769.7 2006.02  1837.4 2005.51
 1860.842009.919    1886 2014.96  2476.6 2016.98  2493.4 2018.82  2545.3 2036.34
#Mann= 17 ,-1 , 0
       0      .1       0    16.1     .12       0   120.6      .1       0
   221.5     .12       0   246.5     .06       0   332.9      .1       0
   482.6     .05       0   718.9     .06       0     768     .05       0
   931.7    .055       0  1032.7     .06       0  1124.9     .05       0
  1632.5    .055       0  1691.8     .06       0  1732.8      .1       0
 1751.81    .045       0 1860.84     .05       0
#XS Ineff= 2 , 0
       0 1077.57 2019.52               0
Permanent Ineff=
       F       F
Bank Sta=1751.81,1860.84
XS Rating Curve= 0 ,0
Exp/Cntr=0.5,0.3

Type RM Length L Ch R = 1 ,77134   ,447.9,440.2,443.9
XS GIS Cut Line= 4
2216917.54310972350452.5544068962215622.58277313350922.717508554
 2215373.9717218351040.7730467322214809.20972797351308.110110477
#Sta/Elev= 30
       0 2045.02    38.2 2026.82    59.1  2023.1     108 2023.46   142.9 2020.72
   245.3 2021.51     358 2019.58     471 2018.37   674.5 2015.31   815.8 2015.88
   900.3 2014.28   924.7 2011.38   977.1  2011.2  1036.6 2010.79  1063.6 2012.78
  1325.3 2011.92  1382.1 2013.75  1400.3 2012.84  1409.2 2010.03  1418.5 2008.27
  1487.5 2008.62  1523.8 2004.03  1574.7 2004.31  1603.7 2010.01  1608.6 2011.64
  1623.4 2013.31  1690.9 2012.28    1738 2013.64  1988.5 2012.22  2277.7 2026.16
#Mann= 11 ,-1 , 0
       0      .1       0   245.3     .05       0     358     .06       0
     471    .055       0   674.5     .06       0   977.1    .055       0
  1063.6     .05       0  1325.3    .055       0  1409.2    .045       0
  1603.7     .05       0  1608.6     .05       0
#XS Ineff= 2 , 0
         1063.95 2024.31
Permanent Ineff=
       F       F
Bank Sta=1409.2,1603.7
XS Rating Curve= 0 ,0
Exp/Cntr=0.5,0.3

Type RM Length L Ch R = 1 ,76694   ,61.4,57.6,52.9
XS GIS Cut Line= 4
2216033.46580964350270.8831823172215391.79911397350550.049618721
2215243.88241506350612.549821809 2214534.2096218351230.332378894
#Sta/Elev= 30
       0 2092.26    11.7 2086.69    18.4 2081.09    67.7 2029.85    86.5 2015.05
    98.3 2011.33   137.7 2011.19   156.3 2013.84   216.4 2010.81     313 2010.56
   323.7 2008.59   330.8 2010.87   647.5 2010.36   699.4 2012.23   717.2 2008.74
   759.9 2006.16  769.252003.187   774.2 2002.88   838.3 2003.36   860.3 2009.11
   895.8 2010.01  1055.5 2007.31    1095    2011  1253.1 2008.72  1329.3 2010.12
  1692.6 2020.37  1707.7 2017.73  1715.9 2019.85  1768.6 2021.39  1801.2 2027.28
#Mann= 8 ,-1 , 0
       0      .1       0   156.3      .1       0     313    .055       0
   330.8     .05       0   647.5    .055       0  769.25    .045       0
   838.3     .12       0   895.8     .05       0
#XS Ineff= 2 , 0
          699.09    2016
Permanent Ineff=
       F       F
Bank Sta=769.25,838.3
XS Rating Curve= 0 ,0
Exp/Cntr=0.5,0.3

Type RM Length L Ch R = 1 ,76636   ,589.8,587.8,583.8
XS GIS Cut Line= 5
2216012.63251796350237.5499156422215341.79921398350500.049718723
2215204.29916088350577.1332259772214951.22945705350767.820836723
2214467.54308847351196.999112234
#Sta/Elev= 30
       0 2092.49    25.1 2078.32    42.7 2055.91    64.6    2032    82.3 2017.78
    99.1 2011.06   140.6 2010.86     159 2013.58   292.9 2010.09   398.5 2010.62
   472.5 2008.82   638.1 2011.41   701.5 2011.94   715.6 2007.63   756.5 2005.62
     759 2005.06     768  2002.7   790.5  2002.5   831.9 2002.75   843.4 2005.16
   865.7 2010.74   888.3 2010.97  1078.6  2006.9  1116.1 2010.02  1337.1 2008.59
  1640.5  2015.5  1709.4 2014.61  1725.6 2017.11  1767.1 2017.14  1841.5 2027.58
#Mann= 9 ,-1 , 0
       0      .1       0   140.6      .1       0   292.9    .055       0
   398.5     .05       0   638.1    .055       0   756.5    .055       0
     759    .045       0   843.4     .12       0   888.3     .05       0
#XS Ineff= 2 , 0
          677.99 2016.58
Permanent Ineff=
       F       F
Bank Sta=759,843.4
XS Rating Curve= 0 ,0
Exp/Cntr=0.5,0.3

Type RM Length L Ch R = 1 ,76048   ,1094.2,1087.7,1070.7
XS GIS Cut Line= 2
2215910.45265291 349418.449886522213679.93688783350884.912147434
#Sta/Elev= 30
       0 2026.02     585 2017.86   608.5 2015.82   670.5 2016.04   824.5 2010.59
  1009.3 2009.56  1024.7 2012.09    1104 2004.97  1118.9  2001.2  1141.9 2001.12
  1179.7 2001.22  1200.7 2005.14  1265.1 2006.77  1296.3 2009.43  1444.8 2008.95
  1559.1 2005.68  1618.8 2007.88  1767.3 2005.47  2168.2 2004.93  2241.1 2001.81
  2255.3 2005.46  2371.8 2004.69  2422.5 2006.09  2461.4 2004.31  2482.7 2007.86
  2497.1 2015.71  2532.5 2039.67  2560.9  2044.8  2610.6 2057.77  2669.4  2070.3
#Mann= 13 ,-1 , 0
       0      .1       0   20.25     .06       0  104.64    .055       0
   183.9     .05       0  540.54     .06       0  597.05     .05       0
  674.87     .06       0  720.15    .055       0   897.1    .055       0
    1104    .045       0  1200.7      .1       0 1322.98     .05       0
 2046.12      .1       0
#XS Ineff= 2 , 0
         1020.37 2013.77
Permanent Ineff=
       F       F
Bank Sta=1104,1200.7
XS Rating Curve= 0 ,0
Exp/Cntr=0.3,0.1

Type RM Length L Ch R = 1 ,74960   ,1063.1,1090,1100.4
XS GIS Cut Line= 4
2215028.65417098348269.2211751492214086.47167213349501.884392232
2214030.91600896349576.8842422222213342.54304188350380.332438484
#Sta/Elev= 30
       0 2020.69   104.7 2008.89   710.5 2008.44     925 2007.39  1046.2 2004.39
  1314.3 2005.65    1341 2008.72  1384.5 2006.32  1442.6 2006.95  1471.5 2000.83
 1515.432002.625  1586.7 1998.09  1623.3 1998.37 1630.84 2002.96  1637.5 2005.22
  1682.7  2003.5  1799.4 2004.37  1872.8 2001.79  1911.7 2004.09  2174.8 2003.11
  2351.3 2000.95  2396.7 1998.35  2412.9 2002.92  2443.1 2001.13  2467.3 2009.41
  2546.8 2011.87  2624.5 2019.85  2640.4 2023.85    2669  2035.2  2702.9 2051.68
#Mann= 13 ,-1 , 0
       0      .1       0  101.09     .05       0  665.08     .06       0
  855.75     .05       0  947.07     .06       0 1370.06    .055       0
 1402.51      .1       0 1515.43    .045       0 1630.84     .12       0
 1800.93     .05       0 2250.82      .1       0 2400.78      .1       0
 2455.87      .1       0
#XS Ineff= 2 , 0
         1340.61 2008.41
Permanent Ineff=
       F       F
Bank Sta=1515.43,1630.84
XS Rating Curve= 0 ,0
Exp/Cntr=0.3,0.1

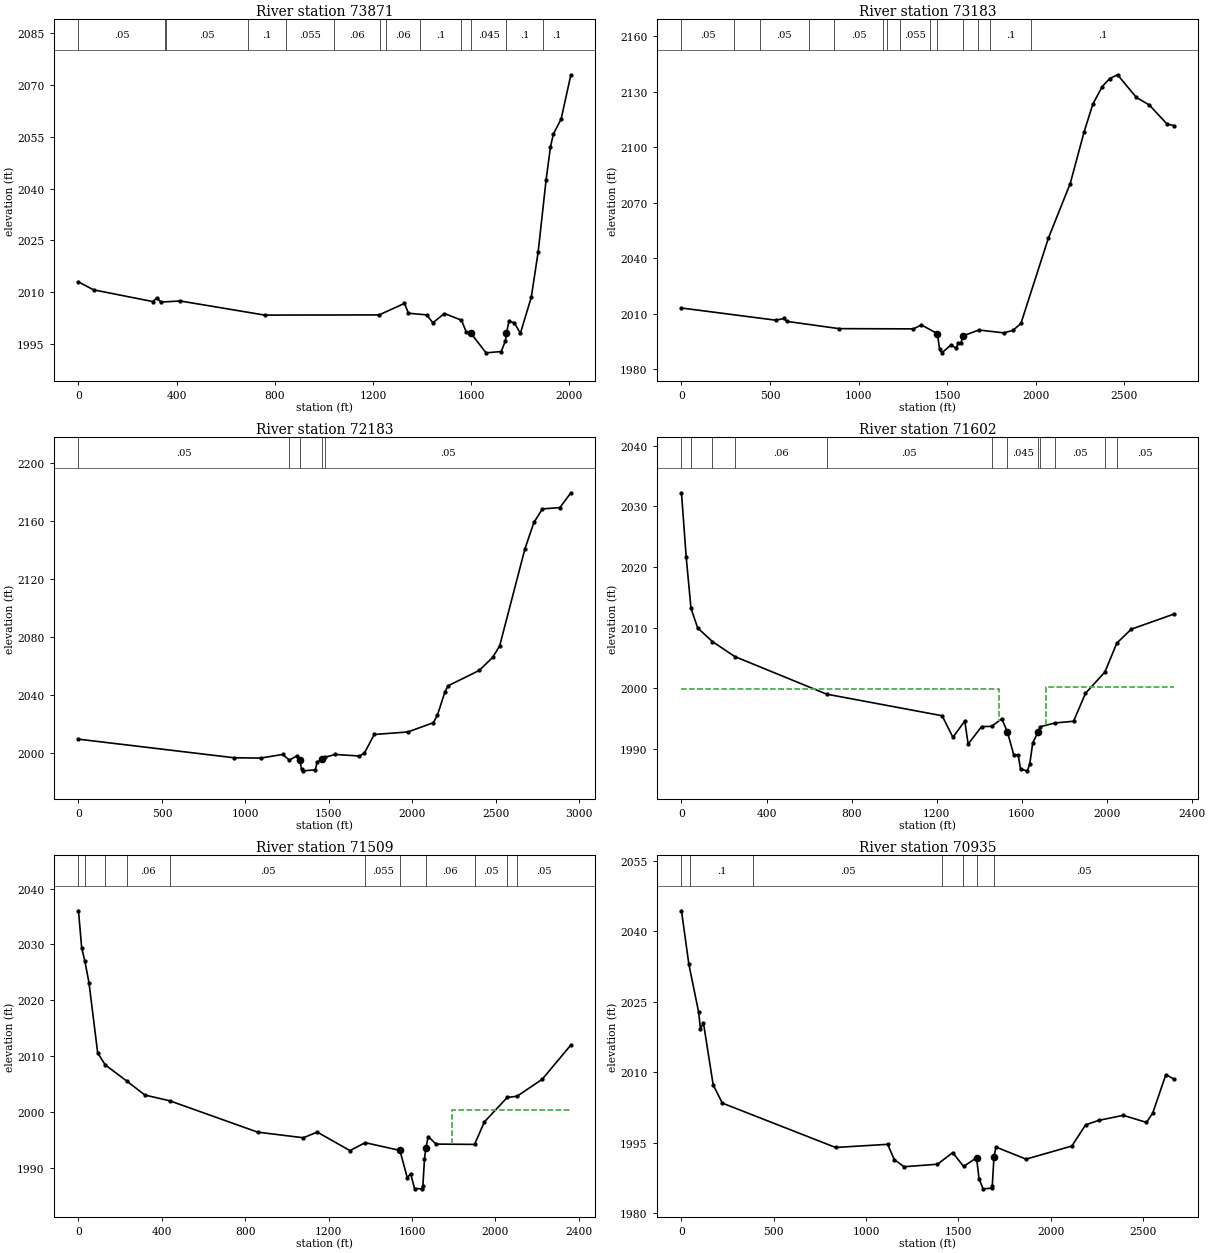
Type RM Length L Ch R = 1 ,73871   ,634.5,687.4,681
XS GIS Cut Line= 4
2214525.87630513348002.5547137262213169.80487031348940.772981644
 2213082.6239423349020.2327964752212895.32083923349169.221343637
#Sta/Elev= 30
       0 2012.99    61.3 2010.69     303 2007.29     319 2008.33   336.2 2007.15
   414.7 2007.46     759 2003.38  1225.2 2003.43  1328.3 2006.77  1344.3 2003.92
  1418.6 2003.44    1444 2001.17  1491.3 2003.84  1560.5  2001.9  1579.7 1998.57
 1599.821998.062  1660.7 1992.46  1722.8 1992.84  1739.8 1996.01 1744.021998.162
  1753.9 2001.58  1775.6 2001.16  1800.7 1998.12  1845.2 2008.62  1873.2 2021.75
  1905.5 2042.57  1923.1 2051.98  1934.9 2055.76  1966.6 2060.09  2006.3  2072.9
#Mann= 13 ,-1 , 0
       0     .05       0  352.71     .06       0  355.94     .05       0
  688.83      .1       0  846.44    .055       0 1041.68     .06       0
 1227.54    .055       0 1252.11     .06       0 1390.44      .1       0
 1559.53      .1       0 1599.82    .045       0 1744.02      .1       0
 1891.35      .1       0
#XS Ineff= 2 , 0
          1326.3  2005.7
Permanent Ineff=
       F       F
Bank Sta=1599.82,1744.02
XS Rating Curve= 0 ,0
Exp/Cntr=0.3,0.1

Type RM Length L Ch R = 1 ,73183   ,1005.9,1000.3,983.2
XS GIS Cut Line= 4
 2214459.2097718347830.3322891442213187.86060847348264.384242564
2212524.63672851348504.9702330772211914.81901984348907.725361853
#Sta/Elev= 30
       0 2013.16   532.6 2006.57   577.7 2007.51     595 2005.94   889.7 2002.02
  1309.2 2001.89  1354.3 2004.03 1444.711999.333  1457.1 1990.94  1469.5 1988.96
  1521.9 1993.22  1549.8 1991.49  1563.7 1994.16  1577.7 1994.26  1588.2 1998.08
  1678.9 2001.28  1818.5 1999.75  1870.9 2001.03  1916.2 2004.81  2071.3 2050.87
  2194.5 2080.32    2273 2108.22  2322.3 2123.23  2375.2 2132.67    2417 2136.97
  2461.7 2139.04  2567.8 2126.82  2641.2 2122.73  2740.8 2112.47  2779.7 2111.62
#Mann= 14 ,-1 , 0
       0     .05       0  297.99     .06       0  442.15     .05       0
  717.77     .06       0  863.62     .05       0 1139.38     .06       0
 1158.08     .05       0 1233.37    .055       0 1405.24      .1       0
 1444.71    .045       0  1588.2      .1       0 1672.64     .05       0
 1742.25      .1       0 1973.75      .1       0
#XS Ineff= 2 , 0
          1351.7 2003.47
Permanent Ineff=
       F       F
Bank Sta=1444.71,1588.2
XS Rating Curve= 0 ,0
Exp/Cntr=0.3,0.1

Type RM Length L Ch R = 1 ,72183   ,590.2,580.8,572.4
XS GIS Cut Line= 4
2213828.65427439346724.7767574792212692.02728255347375.495272309
2212267.94912095347610.896124334 2211385.1364801 348354.93076291
#Sta/Elev= 30
       0 2009.71   931.7 1996.91  1090.5 1996.69  1222.8 1999.19  1263.4 1995.28
  1309.1 1998.29 1326.081995.238    1336 1989.01  1343.5 1987.91  1418.5 1988.57
  1429.8 1993.93 1456.981995.765    1477 1997.29  1538.6 1999.19  1682.9  1998.1
  1712.1    2000  1771.3 2012.93  1973.4 2014.68  2125.7 2021.05  2150.4 2026.38
  2194.6 2042.15  2214.1 2046.47  2400.6 2057.03    2481    2066  2522.8 2073.93
  2674.3 2140.78  2727.8  2158.9    2779 2168.22  2883.8 2169.12  2949.3 2179.31
#Mann= 5 ,-1 , 0
       0     .05       0  1263.4    .055       0 1326.08    .045       0
 1456.98    .055       0    1477     .05       0
Bank Sta=1326.08,1456.98
XS Rating Curve= 0 ,0
Exp/Cntr=0.8,0.6

Type RM Length L Ch R = 1 ,71602   ,91.4,93.1,97.7
XS GIS Cut Line= 5
2213817.54307614346280.3324363982212664.29931964 346689.35524039
2212407.35462356346861.2302247292212254.57704197346972.341551065
2211891.72967055347442.827486724
#Sta/Elev= 30
       0 2032.21    22.1 2021.64    44.7 2013.18    76.1 2009.94   145.5 2007.69
   250.8 2005.22   682.4 1999.03  1225.8 1995.47  1276.7 1991.91  1332.4 1994.61
  1348.2 1990.79  1411.3 1993.68  1458.7 1993.72  1506.1 1994.97 1532.761992.823
  1562.7 1989.03  1583.8    1989  1594.6 1986.65  1626.1 1986.39  1637.8 1987.44
  1651.9 1990.97 1676.071992.732  1687.1 1993.66  1757.5 1994.28    1844 1994.56
  1900.1 1999.16  1991.4 2002.68  2047.5 2007.44  2115.4 2009.73  2315.8 2012.22
#Mann= 12 ,-1 , 0
       0     .12       0    44.7      .1       0   145.5    .055       0
   250.8     .06       0   682.4     .05       0  1458.7    .055       0
 1532.76    .045       0 1676.07     .05       0  1687.1     .06       0
  1757.5     .05       0  1991.4     .06       0  2047.5     .05       0
#XS Ineff= 2 , 0
         1494.06 1999.82 1714.77         2000.13
Permanent Ineff=
       F       F
Bank Sta=1532.76,1676.07
XS Rating Curve= 0 ,0
Exp/Cntr=0.8,0.6

Type RM Length L Ch R = 1 ,71509   ,541.3,574.4,590.7
XS GIS Cut Line= 5
2213792.54312614346227.5546548072212480.27147247 346699.77188623
2212254.57704197346856.0219018162212107.00745521347015.744351387
 2211846.5909813347413.313766226
#Sta/Elev= 30
       0 2036.04    15.5 2029.37      31 2026.96    50.3 2023.18    92.2 2010.56
   128.4 2008.43   231.7 2005.53   318.8 2003.02   437.4    2002   859.3 1996.38
  1078.9 1995.37  1145.2 1996.39  1302.1 1993.07  1375.3 1994.49  1541.71993.109
  1577.4 1988.19  1593.1 1988.96    1612 1986.28  1647.4 1986.22  1651.9 1986.65
  1659.8 1991.59 1665.881993.466  1677.9 1995.58    1715 1994.24    1900 1994.18
    1947 1998.21  2056.8  2002.6  2103.9 2002.81  2224.5 2005.85  2361.9 2011.99
#Mann= 11 ,-1 , 0
       0     .12       0      31      .1       0   128.4    .055       0
   231.7     .06       0   437.4     .05       0  1375.3    .055       0
  1541.7    .045       0 1665.88     .06       0    1900     .05       0
  2056.8     .06       0  2103.9     .05       0
#XS Ineff= 2 , 0
                         1789.76         2000.43
Permanent Ineff=
       F       F
Bank Sta=1541.7,1665.88
XS Rating Curve= 0 ,0
Exp/Cntr=0.8,0.6

Type RM Length L Ch R = 1 ,70935   ,1009.3,993.6,953.3
XS GIS Cut Line= 4
2213706.43174981346160.8877933922212136.47163513346299.106348976
2212013.95121089346315.5265917332211078.65419698346566.443412721
#Sta/Elev= 30
       0 2044.33    40.2 2032.91    92.9 2022.78   102.7 2019.28   119.2 2020.42
   171.9 2007.27   221.4 2003.41   835.1 1993.97  1117.1 1994.64  1152.9  1991.4
  1206.1 1989.87  1387.2 1990.41  1469.5 1992.87  1528.8 1989.94  1598.81991.774
  1612.5 1987.28  1634.5 1985.17  1680.9 1985.31  1684.2 1985.86 1693.141991.955
  1704.1 1994.05  1867.2 1991.49  2115.3 1994.28  2189.9 1998.79  2261.2 1999.74
  2393.7 2000.81  2519.4  1999.3  2553.4 2001.29  2624.7 2009.48    2668 2008.52
#Mann= 7 ,-1 , 0
       0     .12       0   45.85      .1       0  387.09     .05       0
 1413.73     .06       0 1525.34      .1       0  1598.8    .045       0
 1693.14     .05       0
Bank Sta=1598.8,1693.14
XS Rating Curve= 0 ,0
Exp/Cntr=0.3,0.1

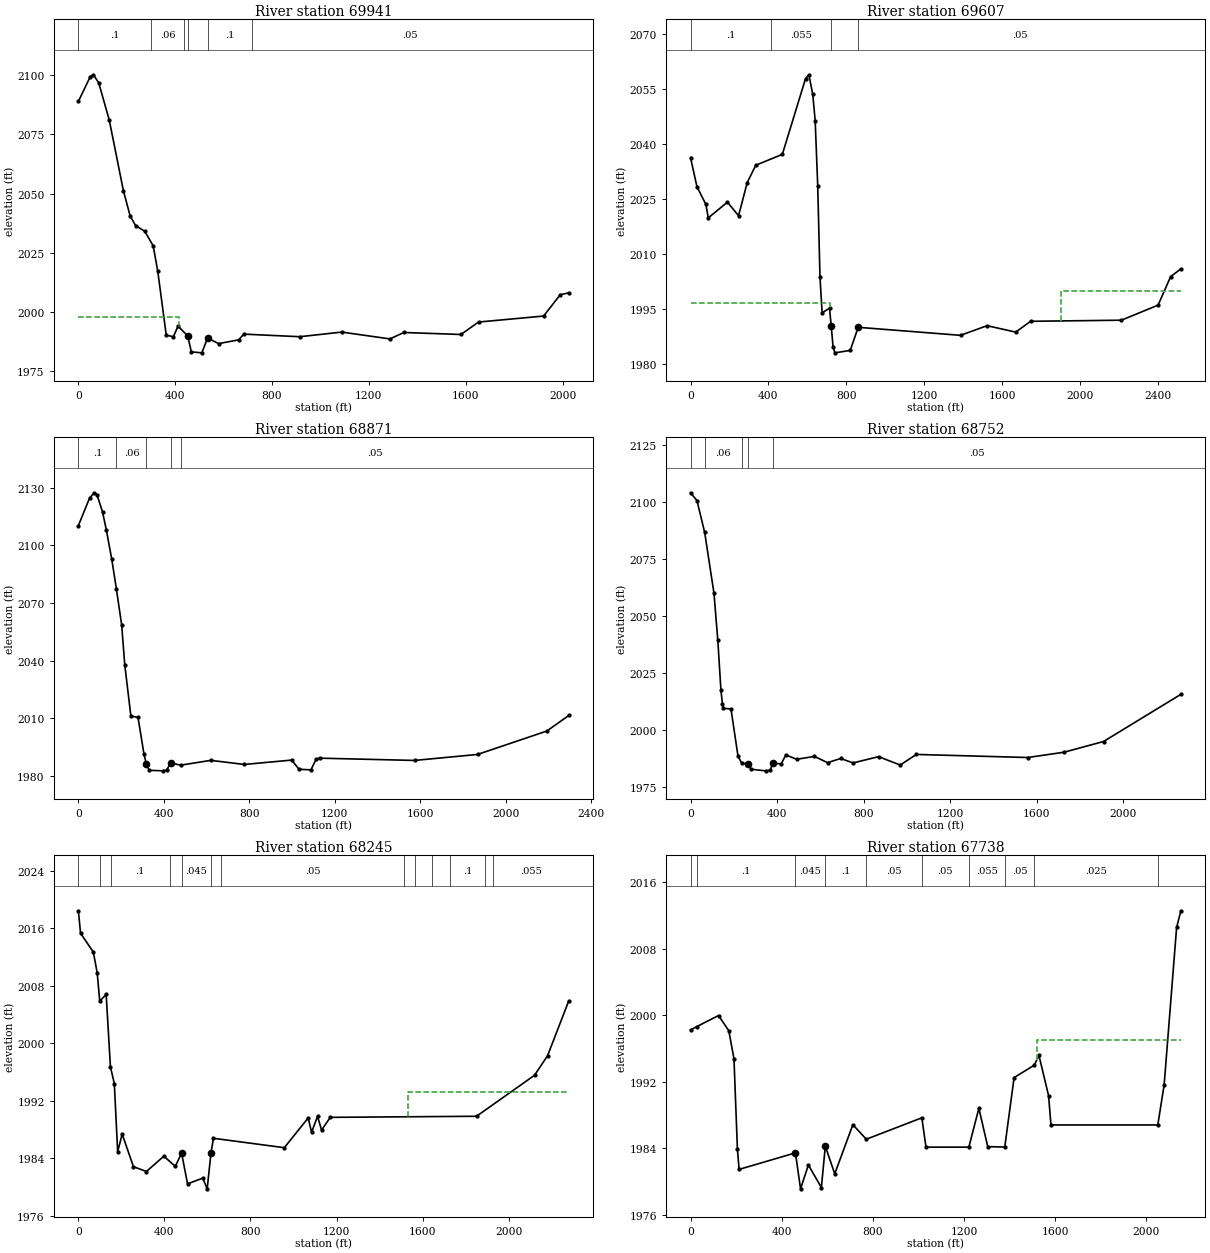
Type RM Length L Ch R = 1 ,69941   ,328.3,334.4,339.5
XS GIS Cut Line= 3
2212349.26845364344988.292697638 2211881.3861873345527.313929304
2211042.54304872346535.888027638
#Sta/Elev= 30
       0 2088.97    49.4 2099.48    62.4 2100.21    84.2 2096.78   127.8 2080.99
   185.8 2051.34   213.7 2040.67   236.2 2036.57   274.2 2034.13   309.1 2027.99
     328 2017.22     363 1990.26   392.6 1989.62   411.4 1994.05  451.83 1989.99
   466.5 1983.23   509.9 1982.81  533.681989.052   579.4  1986.7     662  1988.3
   683.3 1990.71   914.7 1989.62  1087.9 1991.57  1286.9 1988.69  1344.4  1991.4
  1580.4 1990.56  1652.9 1995.81  1921.7 1998.34  1990.4 2007.34  2025.6 2008.14
#Mann= 6 ,-1 , 0
       0      .1       0  300.23     .06       0  435.46      .1       0
  451.83    .045       0  533.68      .1       0  715.12     .05       0
#XS Ineff= 2 , 0
          414.54 1998.12
Permanent Ineff=
       F       F
Bank Sta=451.83,533.68
XS Rating Curve= 0 ,0
Exp/Cntr=0.3,0.1

Type RM Length L Ch R = 1 ,69607   ,757.4,735.6,714.6
XS GIS Cut Line= 3
 2212333.9328817344627.4148353492211889.61757949345028.995251425
2210545.45987713 346398.56374223
#Sta/Elev= 30
       0 2036.31      33 2028.38      79 2023.51    91.1 2019.83   189.5 2024.13
   246.7 2020.43   291.2 2029.48     335  2034.2   471.5 2037.18   590.5 2057.84
   607.9  2058.9   627.7 2053.53   640.1 2046.37   653.2 2028.59   664.8 2003.62
   675.8 1993.93   713.7 1995.18   722.7 1990.19     732 1984.63   741.3    1983
   820.2 1983.66   860.8 1989.97  1386.3 1987.78  1522.7 1990.41  1669.8 1988.66
  1745.9 1991.61  2212.3 1991.91  2400.8 1996.02  2465.1 2003.81  2517.9 2005.91
#Mann= 4 ,-1 , 0
       0      .1       0   411.2    .055       0   722.7    .045       0
   860.8     .05       0
#XS Ineff= 2 , 0
          714.62 1996.64 1899.83            2000
Permanent Ineff=
       F       F
Bank Sta=722.7,860.8
XS Rating Curve= 0 ,0
Exp/Cntr(USF)=0,0
Exp/Cntr=0.5,0.3

Type RM Length L Ch R = 1 ,68871   ,119.2,118.8,118.1
XS GIS Cut Line= 2
2211385.40298807344311.9016796872210457.19489105346411.857621957
#Sta/Elev= 30
       0 2110.18    52.1 2124.41    73.7 2127.26    87.2 2126.23   113.1 2117.28
   131.1 2107.87   156.2 2092.78   177.7 2077.46   202.8 2058.51   217.1 2037.87
   245.8 2011.21   279.3 2010.45   306.8 1991.62   318.71986.046   331.9 1982.97
   395.5 1982.69   413.6 1983.12   432.4 1986.85   478.3 1985.62   620.1 1988.14
     777    1986   999.1 1988.29    1033 1983.51  1088.8  1983.2  1113.9 1988.91
    1130 1989.28  1573.7  1988.1  1868.8 1991.21  2193.6  2003.4  2295.9 2011.47
#Mann= 5 ,-1 , 0
       0      .1       0   177.7     .06       0   318.7    .045       0
   432.4      .1       0   478.3     .05       0
#XS Ineff= 2 , 0
             273  1983.6     477          1983.6
Permanent Ineff=
       F       F
Bank Sta=318.7,432.4
XS Rating Curve= 0 ,0
Exp/Cntr(USF)=0,0
Exp/Cntr=0.5,0.3

Type RM Length L Ch R = 1 ,68752   ,486.2,507.1,522.7
XS GIS Cut Line= 2
2211256.74047957344302.7115005082210360.69800967346384.287084422
#Sta/Elev= 30
       0  2103.9    29.8 2100.51    65.5 2086.51   108.4 2059.87   126.2 2039.21
   140.5  2017.5   147.7 2011.16     152 2009.38     187 2009.14   219.4 1988.45
     237 1985.28   265.5  1985.1   279.8 1982.71   346.7    1982   369.1 1982.22
   379.2 1985.39   419.2 1985.03   440.5 1988.98   490.6 1987.06   572.7 1988.33
   633.4 1985.58   693.8 1987.41   751.3 1985.47   869.2 1988.22   969.2 1984.54
  1043.4 1989.19  1558.6 1987.84  1726.4 1990.17  1908.6 1994.86  2266.2 2015.54
#Mann= 5 ,-1 , 0
       0      .1       0    65.5     .06       0     237      .1       0
   265.5    .045       0   379.2     .05       0
Bank Sta=265.5,379.2
XS Rating Curve= 0 ,0
Exp/Cntr(USF)=0,0
Exp/Cntr=0.5,0.3

Type RM Length L Ch R = 1 ,68245   ,516,506.8,492.8
XS GIS Cut Line= 6
2211007.94633314344054.8739608082210899.61321647344218.763068721
2210306.55764405344831.2628279782209745.24314989 345357.11249806
2209638.41560763345533.5842579752209450.91565456345700.250919387
#Sta/Elev= 30
       0 2018.44    10.1 2015.32    69.6 2012.69    87.4 2009.84    99.3 2005.88
   129.2 2006.81     149 1996.75   167.1 1994.41   182.6 1984.95   203.7 1987.39
     256 1982.86   316.3 1982.19   397.2 1984.32   450.5 1982.91  479.871984.739
   507.5 1980.47   578.1 1981.27   598.8 1979.78   616.21984.696   627.8 1986.81
   957.3  1985.5  1068.4 1989.64  1084.1 1987.64  1111.7 1989.86  1130.6 1987.94
  1170.9 1989.72  1850.8 1989.87  2120.4 1995.57  2180.8 1998.27  2279.6 2005.91
#Mann= 13 ,-1 , 0
       0    .055       0  100.55     .06       0  149.84      .1       0
  425.49      .1       0  479.87    .045       0   616.2      .1       0
  661.31     .05       0 1515.59      .1       0 1566.26    .055       0
 1641.72    .025       0 1727.46      .1       0 1890.54     .05       0
 1928.03    .055       0
#XS Ineff= 2 , 0
                         1531.97         1993.24
Permanent Ineff=
       F       F
Bank Sta=479.87,616.2
XS Rating Curve= 0 ,0
Exp/Cntr=0.3,0.1

Type RM Length L Ch R = 1 ,67738   ,591.8,586.2,545.7
XS GIS Cut Line= 4
2210441.27981555343802.0962511452210091.27985939344438.207511723
2209726.57094313345097.3115084772209361.98735473345661.894696891
#Sta/Elev= 30
       0 1998.22    26.3 1998.61   122.9 1999.96   168.2 1998.12   190.7 1994.73
   205.7 1983.92   213.2 1981.44   460.3 1983.43   482.8  1979.1   517.1 1981.97
   574.1 1979.26   591.4 1984.23   632.7 1980.91   712.3 1986.82   771.2 1985.07
  1014.9 1987.65    1033 1984.12  1221.1 1984.12  1265.1 1988.79    1304 1984.18
  1378.7 1984.13  1419.6 1992.49  1508.4 1993.99  1528.5 1995.17  1570.8 1990.33
  1581.4 1986.79  2050.1 1986.79    2078 1991.64  2132.6 2010.56  2151.4 2012.57
#Mann= 10 ,-1 , 0
       0    .055       0    26.3      .1       0   460.3    .045       0
   591.4      .1       0   771.2     .05       0  1014.9     .05       0
  1221.1    .055       0  1378.7     .05       0  1508.4    .025       0
  2050.1    .055       0
#XS Ineff= 2 , 0
                         1518.65         1997.06
Permanent Ineff=
       F       F
Bank Sta=460.3,591.4
XS Rating Curve= 0 ,0
Exp/Cntr=0.5,0.3