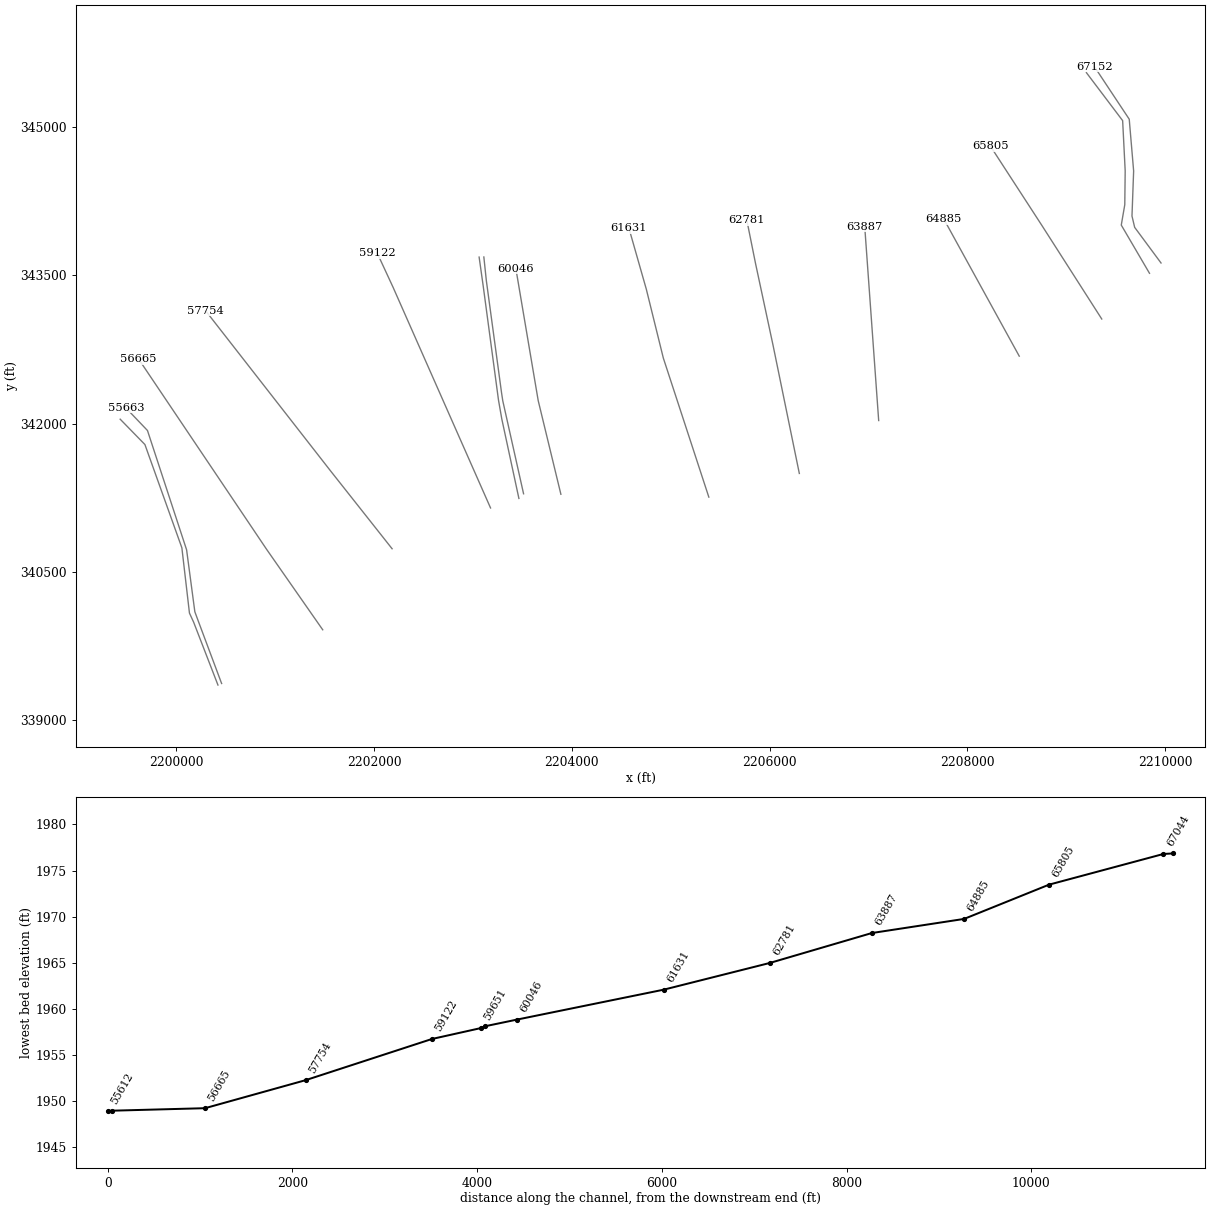
HEC-RAS study ANTHONYCK.prj: ANTHONYCK

--- ANTHONYCK.g01 (geometry) --- (continued)

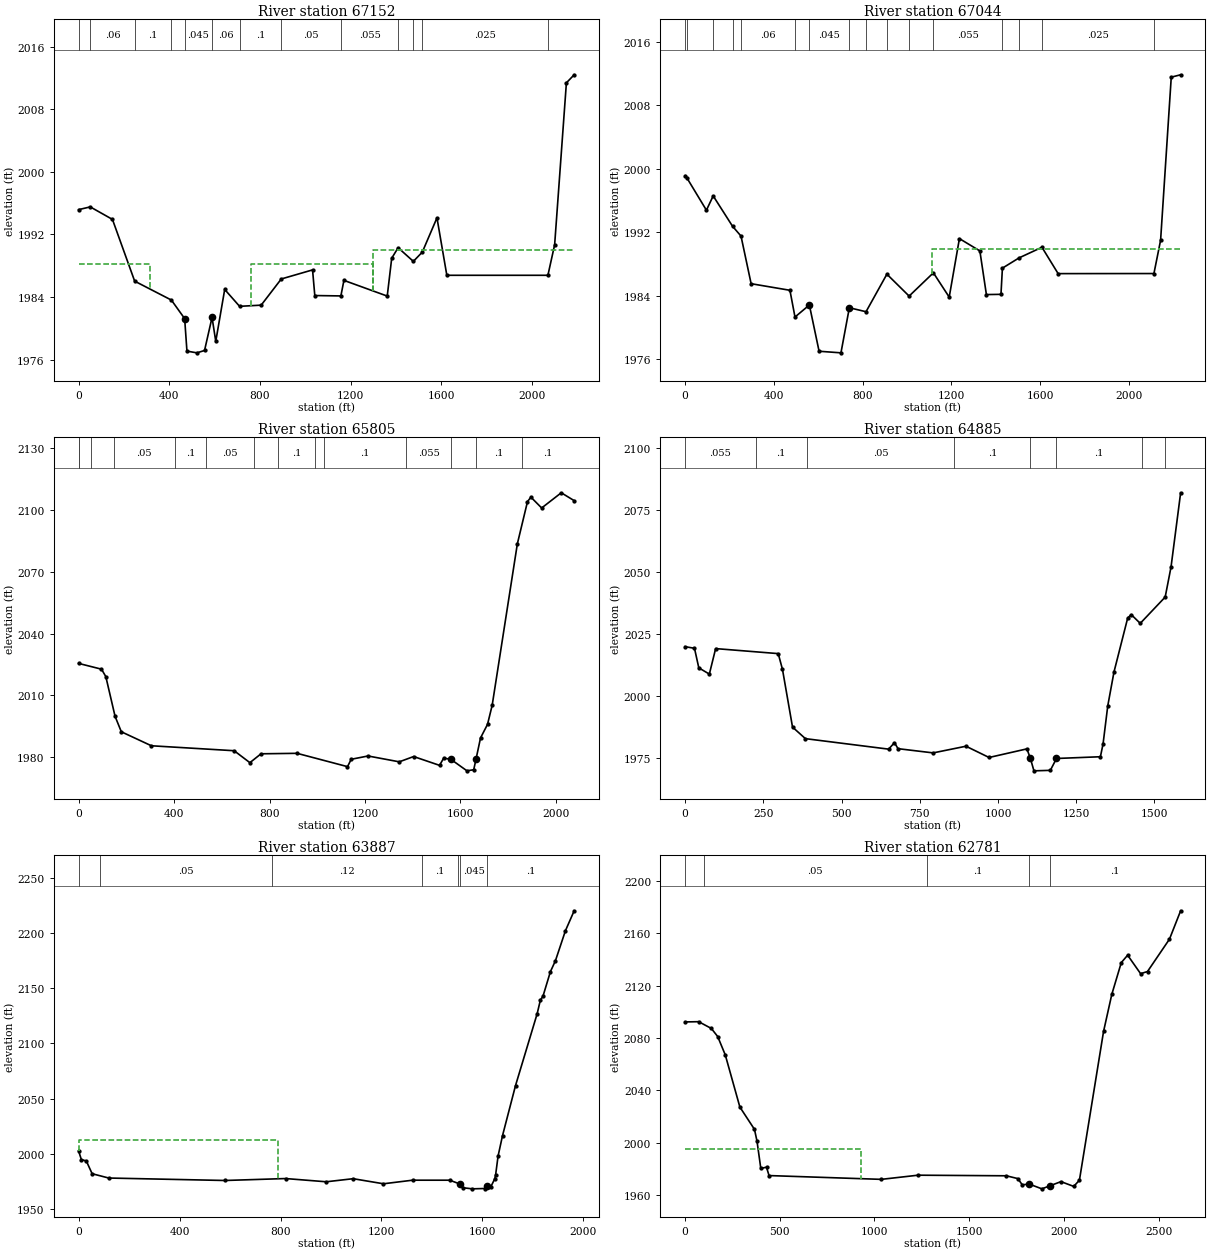
Type RM Length L Ch R = 1 ,67152   ,152.3,108.1,82.4
XS GIS Cut Line= 6
2209958.55834006343626.1956843142209691.89187863343986.612286314
2209664.80859947344101.1957185572209681.47523281344557.445462227
2209636.98746088345080.6448751392209284.90417555345611.894796893
#Sta/Elev= 30
       0 1995.18    51.2 1995.53   149.1 1993.93   247.1 1986.03     409 1983.61
   467.5 1981.24   477.6 1977.08   521.4 1976.86   555.2 1977.16   588.3 1981.39
   604.7 1978.33   644.1 1984.97   709.7 1982.81   804.9 1982.96   893.6 1986.31
  1031.5 1987.47  1041.4 1984.19  1156.4 1984.14  1169.8 1986.13  1360.8 1984.12
  1380.5 1988.96  1408.8 1990.31    1476 1988.56  1515.5 1989.75  1580.1 1994.13
  1623.6 1986.78  2069.3 1986.78    2099 1990.69  2150.8  2011.4  2185.1 2012.43
#Mann= 13 ,-1 , 0
       0    .055       0    51.2     .06       0   247.1      .1       0
     409     .06       0   467.5    .045       0   588.3     .06       0
   709.7      .1       0   893.6     .05       0  1156.4    .055       0
  1408.8     .05       0    1476      .1       0  1515.5    .025       0
  2069.3    .055       0
#XS Ineff= 3 ,-1
       0   313.7  1988.2   761.3    1300  1988.2    1300    2300    1990
Permanent Ineff=
       F       F       F
Bank Sta=467.5,588.3
XS Rating Curve= 0 ,0
Exp/Cntr=0.5,0.3

Type RM Length L Ch R = 1 ,67044   ,1211,1238.7,1237.1
XS GIS Cut Line= 6
2209841.89190672343522.0288978962209556.47515473 344009.52890715
2209591.89175056 344215.778822722209596.05840889344557.445462227
2209570.32092756345066.0615709722209203.65400997345551.478251055
#Sta/Elev= 30
       0 1999.12     8.7 1998.81    96.1 1994.77   126.6 1996.57     214 1992.74
     252 1991.51   297.6 1985.51   472.5 1984.68   495.3 1981.31   560.1 1982.83
   603.9    1977   702.5  1976.8   740.3 1982.48   815.5 1981.98   909.5 1986.71
  1009.7 1983.95  1119.1 1986.88  1190.4 1983.82  1236.4 1991.19  1328.6 1989.64
    1358 1984.14  1423.7 1984.17  1430.2 1987.47  1505.8 1988.77  1608.4  1990.1
  1681.3 1986.78  2113.1 1986.79  2143.2 1990.99  2191.2 2011.53  2233.5 2011.83
#Mann= 16 ,-1 , 0
       0     .05       0     8.7    .055       0   126.6     .06       0
     214     .05       0     252     .06       0   495.3      .1       0
   560.1    .045       0   740.3      .1       0   815.5     .06       0
   909.5    .055       0  1009.7     .05       0  1119.1    .055       0
  1430.2     .05       0  1505.8      .1       0  1608.4    .025       0
  2113.1    .055       0
#XS Ineff= 2 , 0
                         1114.88         1989.87
Permanent Ineff=
       F       F
Bank Sta=560.1,740.3
XS Rating Curve= 0 ,0
Exp/Cntr=0.5,0.3

Type RM Length L Ch R = 1 ,65805   ,913.5,920.2,908.5
XS GIS Cut Line= 3
2209358.97762419343059.6209331932208752.71381248344007.047545275
2208234.63066629 344805.30843539
#Sta/Elev= 30
       0 2025.54    95.8 2022.74   113.9 2019.16   152.7 1999.88   178.9  1992.4
   304.9 1985.62   651.6 1983.22   717.6 1977.43   764.3 1981.73   915.2 1981.96
  1126.6  1975.5  1142.2 1979.07  1212.6 1980.67  1343.5 1977.84  1403.8  1980.4
  1512.3 1976.13  1529.8 1979.66  1560.5 1978.99  1627.2 1973.47  1655.5 1974.01
    1665 1979.07    1684 1989.41  1713.3 1995.99  1732.8 2005.23  1838.4 2083.55
  1880.8 2103.96  1895.1 2106.13  1940.2 2100.87  2022.3 2108.24  2076.4 2104.43
#Mann= 14 ,-1 , 0
       0     .05       0     1.1    .055       0   49.95     .06       0
  146.73     .05       0   402.3      .1       0  534.84     .05       0
  732.76      .1       0  835.66      .1       0  992.49     .12       0
 1029.45      .1       0 1371.67    .055       0  1560.5    .045       0
    1665      .1       0 1856.92      .1       0
Bank Sta=1560.5,1665
XS Rating Curve= 0 ,0
Exp/Cntr=0.3,0.1

Type RM Length L Ch R = 1 ,64885   ,1014.1,998.4,977.6
XS GIS Cut Line= 2
2208524.48738931342684.1171878872207761.05814189 344071.52681464
#Sta/Elev= 30
       0 2019.77      30 2019.13    43.8 2011.24    77.5 2008.73    97.6    2019
   297.6 2016.98   311.2 2010.63   343.3 1987.37   384.5 1982.72   650.4 1978.49
   669.1  1981.1   680.4 1978.68   792.7 1976.98   897.6 1979.67   971.4 1975.13
  1092.3  1978.6  1103.5 1974.74  1114.8 1969.75  1167.2 1969.95 1186.871974.731
  1327.2 1975.43  1335.7  1980.6  1350.7 1995.93  1370.6 2009.59  1414.3 2031.28
  1425.6 2032.71  1454.5 2029.17  1534.2 2039.76  1552.9 2051.89  1583.6 2081.78
#Mann= 8 ,-1 , 0
       0    .055       0  225.38      .1       0  388.47     .05       0
  860.57      .1       0  1103.5    .045       0 1186.87      .1       0
 1458.79      .1       0 1534.75      .1       0
Bank Sta=1103.5,1186.87
XS Rating Curve= 0 ,0
Exp/Cntr=0.3,0.1

Type RM Length L Ch R = 1 ,63887   ,1098.7,1105.9,1113.2
XS GIS Cut Line= 2
2207102.72481288342032.6378478112206961.76577722343990.985309064
#Sta/Elev= 30
       0 2002.49    10.7  1994.8    30.5 1993.47    53.5 1981.92   119.3 1978.02
   579.8 1975.79   819.9 1977.55   981.1 1974.62  1087.7 1977.41  1207.9 1972.81
  1323.2 1976.06  1470.5 1976.05 1511.081972.561  1523.8 1969.18    1560 1968.22
  1609.3 1968.52 1619.251970.959  1632.4 1969.73  1648.8 1977.35  1652.1 1980.75
  1661.9 1997.97  1679.6 2016.56    1731 2061.84  1816.6 2126.88  1829.7  2139.5
  1839.6  2142.7  1869.2  2165.1  1889.1    2175  1928.9 2202.32  1963.4 2220.33
#Mann= 7 ,-1 , 0
       0     .06       0   85.33     .05       0  765.96     .12       0
 1361.95      .1       0 1503.27      .1       0 1511.08    .045       0
 1619.25      .1       0
#XS Ineff= 2 , 0
          790.04 2012.94
Permanent Ineff=
       F       F
Bank Sta=1511.08,1619.25
XS Rating Curve= 0 ,0
Exp/Cntr=0.3,0.1

Type RM Length L Ch R = 1 ,62781   ,1136.8,1149.5,1145.1
XS GIS Cut Line= 4
2206300.07293269 341497.479217962206034.24893147342794.000826389
2205857.56427005343619.1129373992205768.83756274344059.911844871
#Sta/Elev= 30
       0 2092.27    71.6 2092.46   138.6  2087.3   172.1 2081.14   212.2 2067.11
   289.3 2027.33   366.3 2010.35   379.7  2001.4   399.8 1980.52   429.9 1981.48
   443.3 1975.09  1036.1  1972.2  1230.4 1975.38  1696.6 1974.92    1757 1972.79
  1780.5 1968.05  1817.4  1968.6  1884.2 1964.97  1924.7  1967.2  1985.1 1970.47
  2052.2 1966.83  2082.4 1971.55  2209.8    2085  2253.3 2113.26  2303.5 2137.53
    2337 2143.17  2405.5 2129.07  2441.9 2130.72  2557.9 2155.41  2616.9 2177.05
#Mann= 5 ,-1 , 0
       0     .06       0   99.12     .05       0 1275.13      .1       0
  1817.4    .045       0  1924.7      .1       0
#XS Ineff= 2 , 0
          928.13 1995.18
Permanent Ineff=
       F       F
Bank Sta=1817.4,1924.7
XS Rating Curve= 0 ,0
Exp/Cntr=0.3,0.1

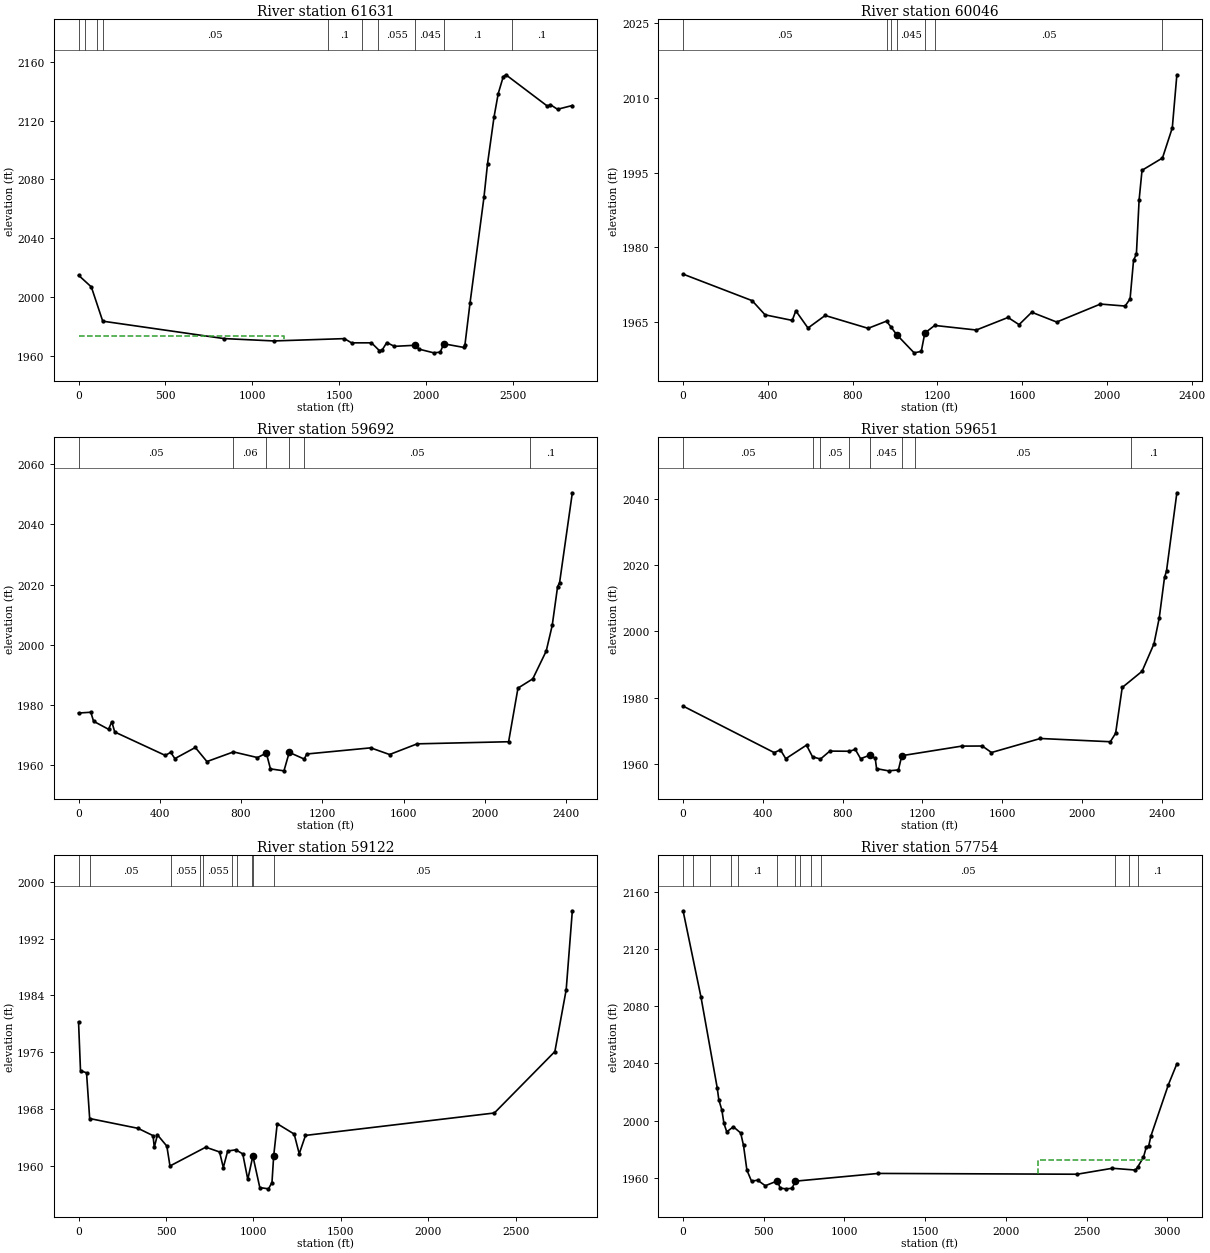
Type RM Length L Ch R = 1 ,61631   ,1562.4,1585.4,1558.7
XS GIS Cut Line= 4
2205384.74114014341258.1965504072204924.48737147342664.672672972
2204752.40667924343361.2573055922204576.32063951343978.962454458
#Sta/Elev= 30
       0 2014.86    73.6 2006.89   139.1 1983.61   836.5 1971.77    1123 1970.16
  1528.8 1971.74  1569.8 1968.87  1684.7 1968.88  1729.4 1963.65  1745.6 1963.91
  1772.6 1969.06  1816.5 1966.48  1937.5 1967.23    1957 1964.61  2042.9 1962.07
  2080.1 1962.54  2100.4 1968.22  2215.5 1965.75  2222.1 1967.49  2251.3 1995.92
  2331.4 2067.75  2351.9 2090.61  2389.4  2122.5  2413.5 2138.41  2442.4  2149.9
  2457.7 2151.21  2696.5 2129.87  2713.5 2130.89  2754.5 2127.74  2839.7 2130.31
#Mann= 10 ,-1 , 0
       0     .12       0   38.71     .06       0  107.77    .055       0
  139.81     .05       0 1433.96      .1       0 1629.03      .1       0
 1724.49    .055       0  1937.5    .045       0  2100.4      .1       0
 2493.26      .1       0
#XS Ineff= 2 , 0
         1179.87 1973.65
Permanent Ineff=
       F       F
Bank Sta=1937.5,2100.4
XS Rating Curve= 0 ,0
Exp/Cntr=0.3,0.1

Type RM Length L Ch R = 1 ,60046   ,351.8,353.9,355.6
XS GIS Cut Line= 3
2203888.37625472341286.894916728 2203659.0128683342233.774584651
2203432.82073538343570.228276566
#Sta/Elev= 30
       0 1974.63     326  1969.3   386.7 1966.46     515 1965.34   531.9 1967.26
   589.3 1963.81   670.3 1966.33   872.9 1963.75   959.8 1965.19   981.9 1963.96
  1007.4  1962.5    1090 1958.83  1123.8 1959.12  1140.5  1962.8  1187.1 1964.33
  1383.4 1963.41  1533.1 1965.93  1585.2 1964.49    1645 1966.98  1762.7 1965.01
    1969 1968.62  2085.5 1968.22  2108.9 1969.65  2125.4 1977.45  2138.7 1978.61
  2151.5  1989.5  2165.3 1995.47  2261.8 1997.94  2308.1 2003.99  2329.7 2014.64
#Mann= 7 ,-1 , 0
       0     .05       0   959.8      .1       0   981.9    .025       0
  1007.4    .045       0  1140.5      .1       0  1187.1     .05       0
  2261.8      .1       0
Bank Sta=1007.4,1140.5
XS Rating Curve= 0 ,0
Exp/Cntr=0.5,0.3

Type RM Length L Ch R = 1 ,59692   ,50.7,41.4,45.2
XS GIS Cut Line= 5
2203510.87635355341292.0336859822203300.50275855342232.642369062
2203288.00278355342314.5867589712203134.33568792343448.100486808
2203109.16262964343687.007535231
#Sta/Elev= 30
       0  1977.3    60.5 1977.56    73.9 1974.57   147.9 1971.89   163.7  1974.4
   178.2    1971   426.9 1963.22   453.8 1964.24   474.1 1962.15   574.9 1965.85
     632 1961.17   762.6 1964.38   880.9  1962.5  924.511963.992   944.7 1958.74
  1011.3 1958.09 1037.181964.226  1110.8 1962.01  1123.9 1963.69  1438.5 1965.73
  1531.2 1963.51  1666.9 1967.06  2117.2 1967.76  2163.3 1985.58  2236.2 1988.66
  2302.2 1997.87  2331.9 2006.41  2358.3 2019.28  2368.2 2020.65  2430.9 2050.49
#Mann= 6 ,-1 , 0
       0     .05       0   762.6     .06       0  924.51    .045       0
 1037.18      .1       0  1110.8     .05       0  2223.3      .1       0
#XS Ineff= 2 ,-1
       0   909.5 1959.78 1053.18  2254.7 1959.78
Permanent Ineff=
       F       F
Bank Sta=924.51,1037.18
XS Rating Curve= 0 ,0
Exp/Cntr=0.5,0.3

Type RM Length L Ch R = 1 ,59651   ,509.9,528.2,544.6
XS GIS Cut Line= 5
2203463.65400705341244.8113394832203290.78066514342047.919969484
2203257.44739847342238.1978041382203103.13044894343389.590663725
2203061.34951678343685.943521383
#Sta/Elev= 30
       0 1977.44   457.2 1963.39   487.9 1964.25   514.8 1961.56   618.8 1965.66
     649 1962.13   688.9 1961.46   735.7 1963.86   833.5 1963.81   863.5 1964.35
   890.1 1961.56   936.11962.642   963.4 1961.69   970.1 1958.56  1029.9  1957.9
  1079.6 1958.17 1096.591962.471  1396.9 1965.36    1500 1965.39  1546.3 1963.43
  1791.3 1967.66  2142.1 1966.68  2168.6 1969.24  2201.7 1983.05  2301.2 1987.94
  2360.8 1996.21  2387.3 2004.03  2413.8 2016.29  2423.7 2018.18  2475.7  2041.8
#Mann= 8 ,-1 , 0
       0     .05       0     649    .055       0   688.9     .05       0
   833.5     .06       0   936.1    .045       0 1096.59     .06       0
  1160.4     .05       0    2247      .1       0
Bank Sta=936.1,1096.59
XS Rating Curve= 0 ,0
Exp/Cntr=0.5,0.3

Type RM Length L Ch R = 1 ,59122   ,1348.9,1368.2,1377.4
XS GIS Cut Line= 3
 2203176.8484783 341148.515272232202190.37720885343381.789353981
2202029.96770288343727.786711128
#Sta/Elev= 30
       0 1980.26    11.2 1973.38    45.7 1973.07    63.6 1966.63   339.8 1965.25
   425.9 1964.22     433 1962.57     451 1964.33   504.8 1962.74   522.7 1959.94
   727.2 1962.59   806.1 1961.92   827.6 1959.72   852.7 1962.05   899.4 1962.22
   938.8 1961.64   967.5 1958.05  996.551961.351  1036.2  1956.9  1085.9 1956.72
  1105.8 1957.61 1115.451961.344  1135.7  1965.9  1232.7 1964.44  1261.6 1961.66
  1297.4 1964.25  2377.1 1967.41    2723 1976.07  2787.7 1984.79  2822.8 1995.91
#Mann= 10 ,-1 , 0
       0     .06       0   65.66     .05       0  530.14    .055       0
  696.41     .05       0  713.96    .055       0  876.83      .1       0
  903.05      .1       0  992.71    .055       0  996.55    .045       0
 1115.45     .05       0
Bank Sta=996.55,1115.45
XS Rating Curve= 0 ,0
Exp/Cntr=0.3,0.1

Type RM Length L Ch R = 1 ,57754   ,1087,1088.9,1081.6
XS GIS Cut Line= 3
2202181.23498397340735.7870948852201559.16007411341522.600453162
2200294.05609297343144.416155677
#Sta/Elev= 30
       0 2146.78     111 2086.35   211.4 2022.97   221.5 2014.55   240.2 2007.44
   253.2 1998.01   270.6 1992.13   311.7 1995.66     357 1991.34   374.5  1982.6
   395.4 1965.38   424.1 1957.59   461.8 1958.32   509.5 1954.42   583.5 1957.78
   602.2 1952.73   637.3 1952.25   674.7 1952.61   696.5 1957.63  1209.7 1963.03
  2441.5 1962.47  2660.3 1966.64  2803.5 1965.38  2817.9 1967.64    2853 1974.41
  2870.1 1981.31  2885.7 1982.44  2899.2 1989.27  3007.4 2025.13  3059.9 2039.74
#Mann= 13 ,-1 , 0
       0    .055       0   60.84     .06       0  165.25    .055       0
  298.54      .1       0  341.13      .1       0   583.5    .045       0
   696.5      .1       0  727.58     .05       0  792.92      .1       0
     852     .05       0 2675.61      .1       0 2761.83     .05       0
  2817.9      .1       0
#XS Ineff= 1 ,-1
 2202.04  2891.2 1972.56
Permanent Ineff=
       F
Bank Sta=583.5,696.5
XS Rating Curve= 0 ,0
Exp/Cntr=0.3,0.1

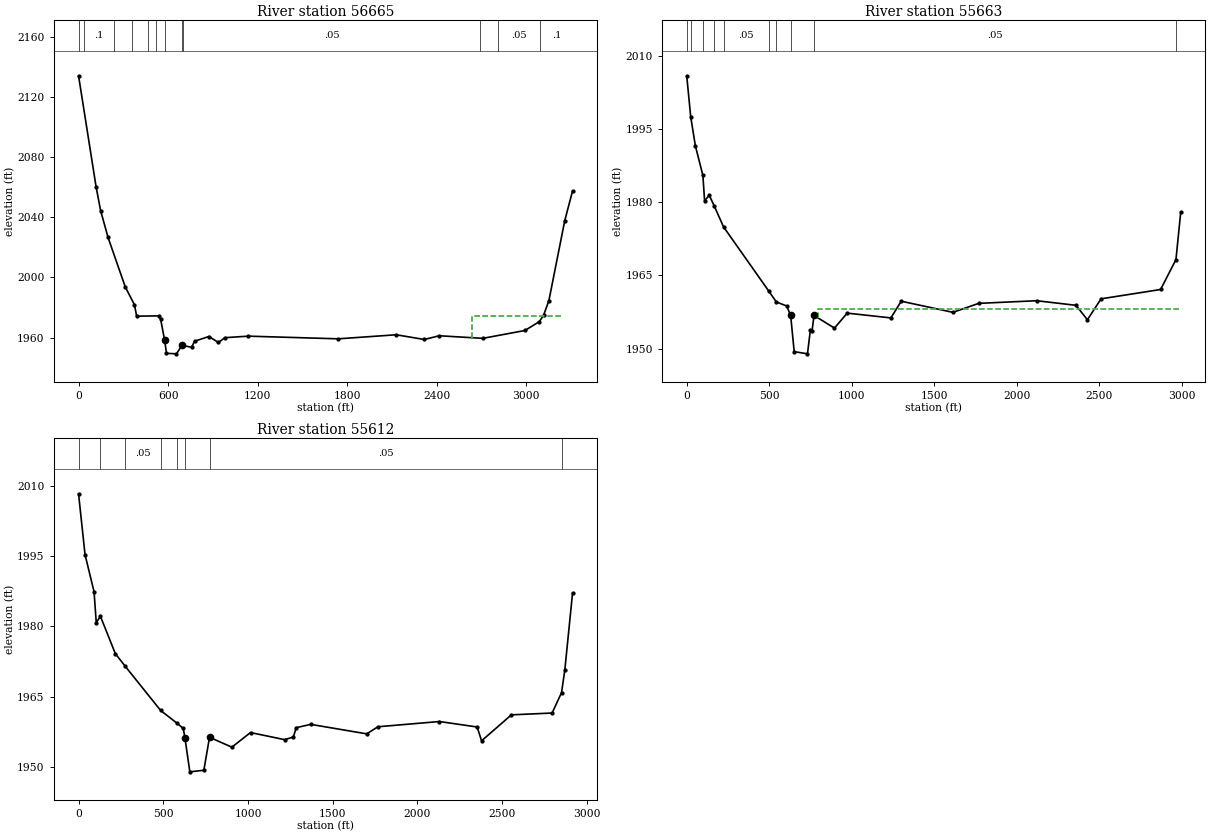
Type RM Length L Ch R = 1 ,56665   ,1012.9,1002.4,987.9
XS GIS Cut Line= 3
2201479.33134909339916.3121824752200911.34830052 340730.58555557
2199618.03730595342653.800280686
#Sta/Elev= 30
       0 2133.97   117.3 2060.33   147.7 2044.44   197.2 2026.69   313.3 1993.59
   374.8  1981.8   389.3 1974.24   537.3 1974.44   549.3 1972.58   576.6 1958.45
   589.3 1949.56   655.8 1949.21   693.3 1954.84   757.3 1953.58   777.3 1957.58
   873.3 1960.73   937.1 1956.78   981.3 1959.95  1137.9 1960.96  1740.5 1959.19
  2128.9 1961.88  2317.8 1958.74  2416.6 1961.22  2709.2 1959.51  2991.2 1964.72
  3087.3 1970.58  3116.5 1974.87    3152 1984.63  3258.3 2037.76  3310.4 2057.43
#Mann= 12 ,-1 , 0
       0      .1       0    35.2      .1       0   240.6    .055       0
   357.6      .1       0   462.7    .055       0   519.5      .1       0
   576.6    .045       0   693.3      .1       0   698.1     .05       0
  2691.9     .07       0  2809.3     .05       0  3095.5      .1       0
#XS Ineff= 1 ,-1
 2636.39  3234.7 1974.47
Permanent Ineff=
       F
Bank Sta=576.6,693.3
XS Rating Curve= 0 ,0
Exp/Cntr=0.5,0.3

Type RM Length L Ch R = 1 ,55663   ,47.5,50.5,55.1
XS GIS Cut Line= 6
2200456.75286864339372.9896238152200221.33634472340002.850568816
2200185.91942081340098.6840385652200102.62299947340724.896368816
2199706.81834489341931.8480231462199488.06845431342161.014559567
#Sta/Elev= 30
       0  2005.9    24.2 1997.49    52.3 1991.57    97.8  1985.5   108.3 1980.31
   136.7 1981.42   167.8 1979.15   223.3 1974.94   498.7 1961.72   542.6 1959.58
   605.7 1958.74  629.781956.799   651.2 1949.39   731.7 1948.94   749.2 1953.83
   759.6 1953.68  771.391956.805   895.2 1954.21   972.3 1957.28    1237  1956.3
  1299.9 1959.72    1613 1957.44  1769.3 1959.28  2120.5 1959.82  2358.8 1958.88
  2427.8 1955.92  2510.7 1960.21  2871.4 1962.12  2964.4 1968.24  2993.3 1977.93
#Mann= 10 ,-1 , 0
       0      .1       0    24.2     .06       0    97.8    .055       0
   167.8      .1       0   223.3     .05       0   498.7      .1       0
   542.6      .1       0  629.78    .045       0  771.39     .05       0
  2964.4      .1       0
#XS Ineff= 2 , 0
          604.78  1958.1  796.39          1958.1
Permanent Ineff=
       F       F
Bank Sta=629.78,771.39
XS Rating Curve= 0 ,0
Exp/Cntr=0.5,0.3

Type RM Length L Ch R = 1 ,55612   ,719.5,690.4,667.1
XS GIS Cut Line= 6
2200419.71586922339357.3646550632200173.18814705339994.517252147
2200131.52156372340084.7952868042200054.74153355340745.438322484
2199680.99949889341789.8220604812199430.77690221342046.431455389
#Sta/Elev= 30
       0  2008.4    38.2 1995.38    91.5 1987.43   104.4 1980.82     129 1982.18
     217 1974.19   273.3 1971.57   484.3 1962.02   579.3 1959.34     618 1958.16
  627.611956.214   656.7 1948.88   739.4 1949.22  772.991956.278   904.7 1954.16
  1014.9 1957.29  1216.1 1955.77    1268 1956.34  1284.5 1958.34  1370.4 1959.04
  1700.7 1957.01  1766.9 1958.53  2129.7 1959.65  2352.3 1958.48  2378.6 1955.52
  2554.4 1961.08  2794.8 1961.47  2850.4 1965.83  2869.8 1970.69  2915.4 1987.15
#Mann= 8 ,-1 , 0
       0     .06       0     129      .1       0   273.3     .05       0
   484.3      .1       0   579.3      .1       0  627.61    .045       0
  772.99     .05       0  2850.4      .1       0
Bank Sta=627.61,772.99
XS Rating Curve= 0 ,0
Exp/Cntr=0.5,0.3