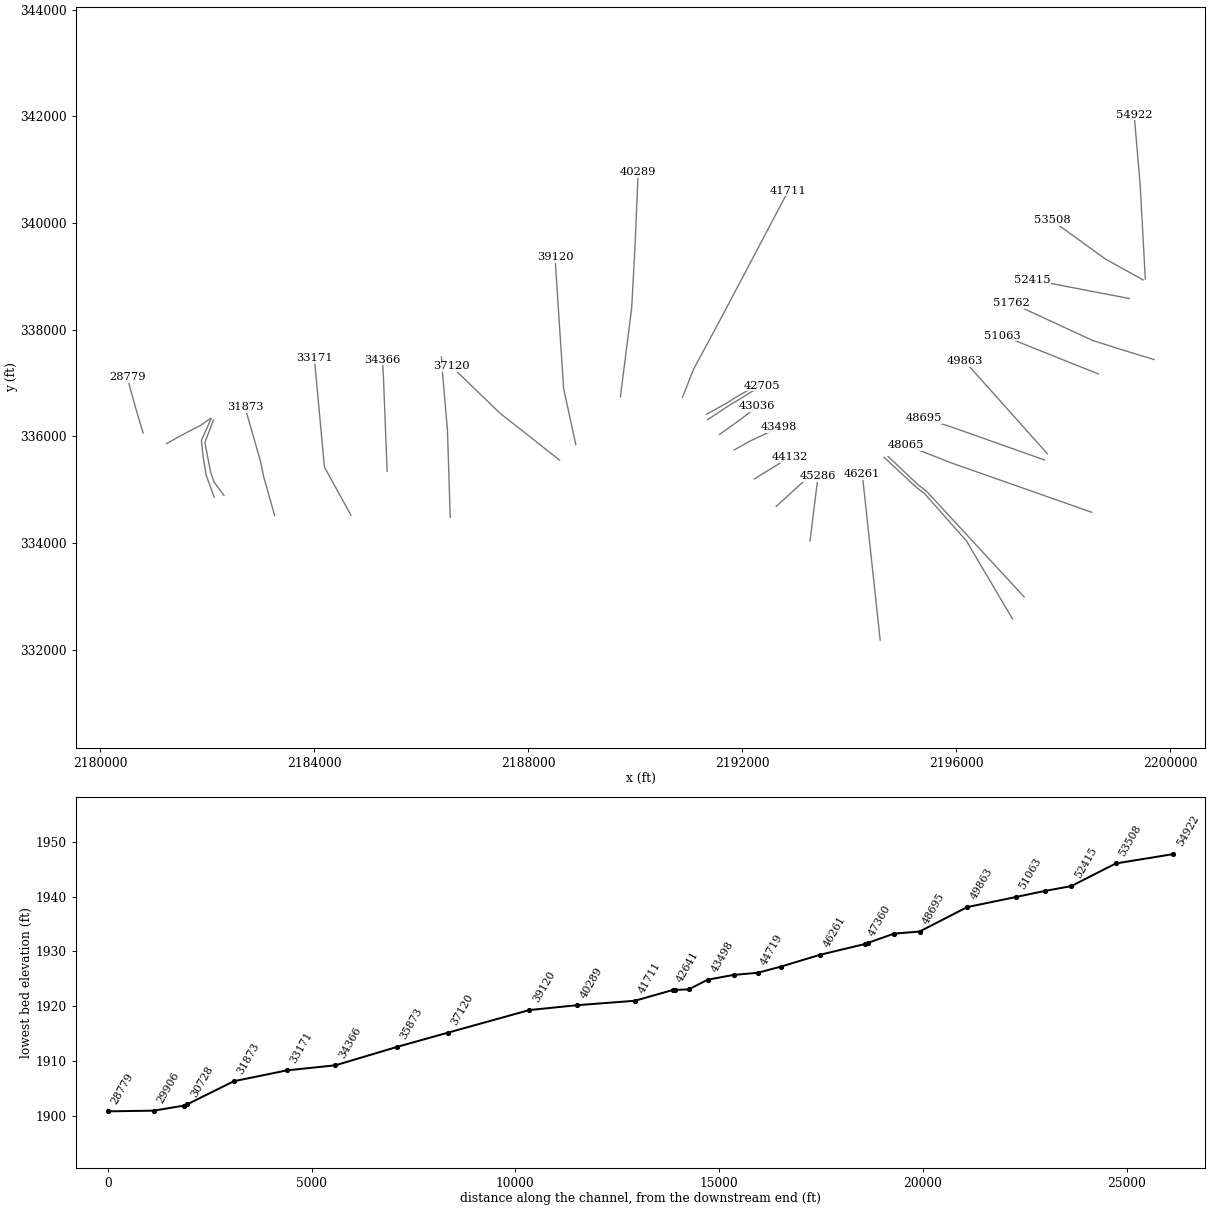
HEC-RAS study ANTHONYCK.prj: ANTHONYCK

--- ANTHONYCK.g01 (geometry) --- (continued)

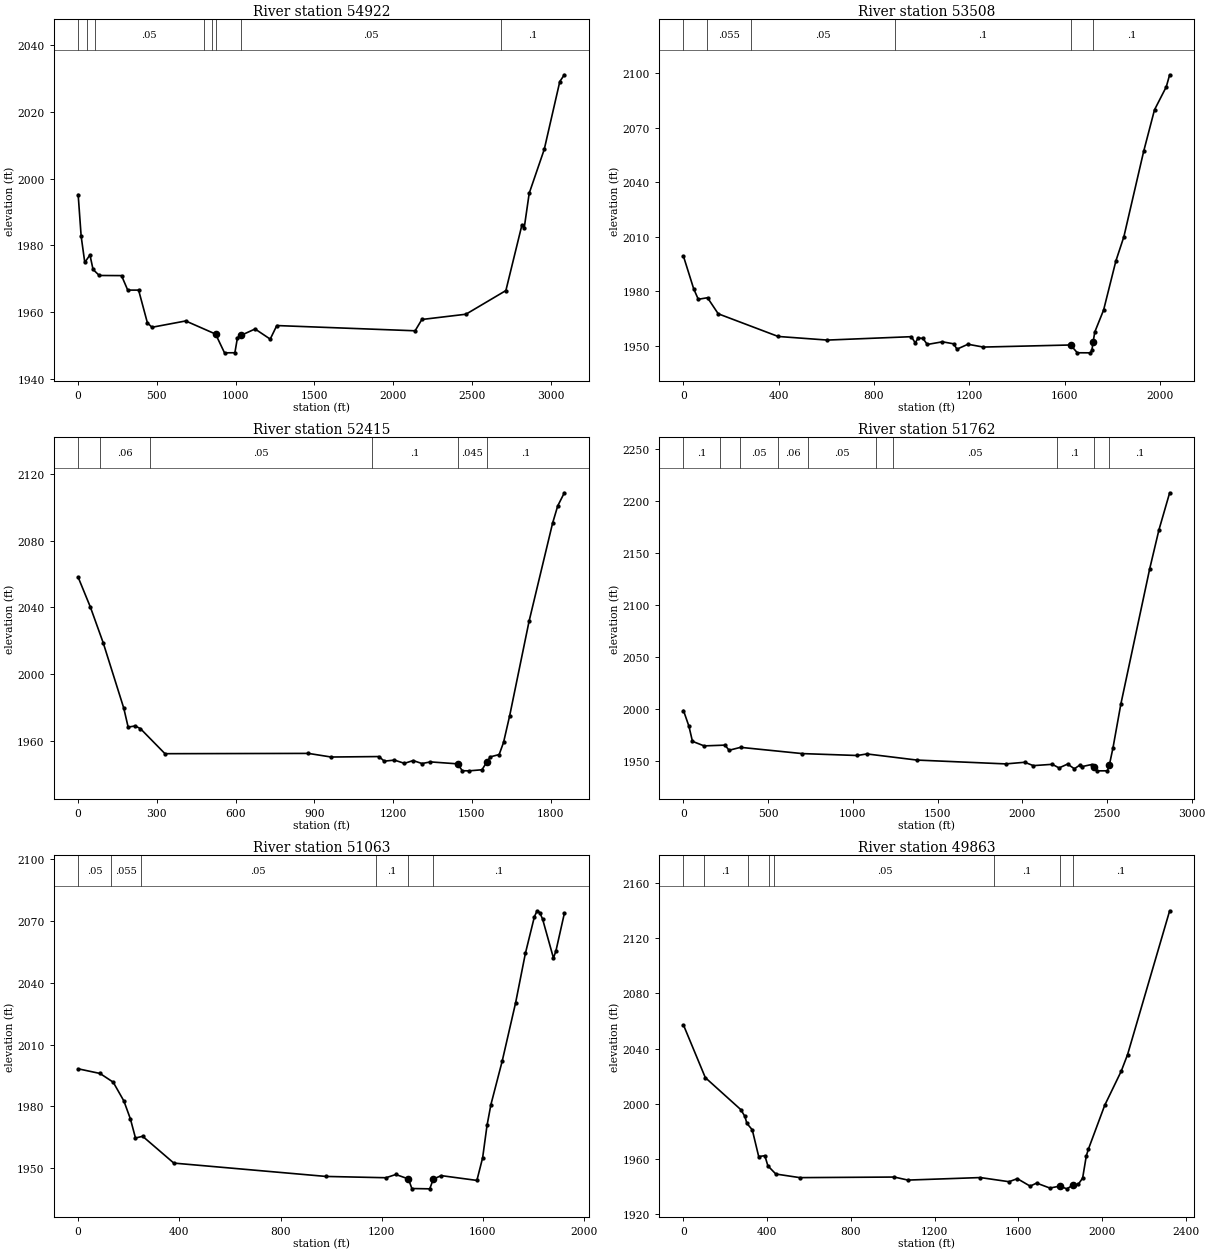
Type RM Length L Ch R = 1 ,54922   ,1368.2,1414.4,1448.3
XS GIS Cut Line= 3
2199534.48732471338950.2512960582199438.64663714340702.529287562
2199326.15407997342029.418037981
#Sta/Elev= 30
       0 1995.23      19 1982.74      42 1974.88    74.8 1977.14    94.5 1972.78
     134 1970.97   275.3 1970.93   314.7 1966.58   383.7 1966.58   439.5 1956.76
   468.4 1955.42   682.7 1957.32  872.53 1953.38   929.1 1947.75   994.9 1947.78
  1011.3 1952.31 1032.791952.971    1123 1954.91  1219.2 1951.87    1261 1955.94
  2139.1 1954.37  2181.9 1957.76  2461.7 1959.34  2715.3 1966.44  2817.3 1986.15
  2831.7 1985.23  2863.4 1995.64  2958.9 2008.82  3057.7 2029.19  3086.5 2031.21
#Mann= 8 ,-1 , 0
       0     .06       0   58.59    .055       0  104.11     .05       0
  797.12      .1       0  849.53      .1       0  872.53    .045       0
 1032.79     .05       0 2684.92      .1       0
Bank Sta=872.53,1032.79
XS Rating Curve= 0 ,0
Exp/Cntr=0.3,0.1

Type RM Length L Ch R = 1 ,53508   ,1056.1,1092.3,1102.1
XS GIS Cut Line= 3
2199492.82074139338933.5846627212198788.65417072339325.251202226
2197788.65420222340050.251392648
#Sta/Elev= 30
       0 1999.21    42.8 1981.33    62.1 1975.54   100.9 1976.39   145.9 1967.54
   397.4 1955.06     604 1953.07   956.7 1954.94   972.9 1951.48   985.1 1954.27
  1005.3 1953.96  1023.5 1950.65    1087 1952.12    1134 1951.01  1148.1 1948.06
  1194.1 1950.77  1258.5 1949.22 1624.831950.367  1653.2 1946.08  1708.3 1946.04
  1714.5 1947.57 1719.851952.183  1726.6 1957.52  1763.6 1969.61  1815.2 1996.66
  1848.7 2009.99  1931.9 2057.07  1977.3 2079.89  2026.7 2092.55  2040.9 2099.18
#Mann= 6 ,-1 , 0
       0     .06       0   97.19    .055       0  283.21     .05       0
   888.9      .1       0 1624.83    .045       0 1719.85      .1       0
Bank Sta=1624.83,1719.85
XS Rating Curve= 0 ,0
Exp/Cntr=0.3,0.1

Type RM Length L Ch R = 1 ,52415   ,666.8,653.5,638.1
XS GIS Cut Line= 2
2199234.01286006338585.1634435652197415.26288864338935.163399726
#Sta/Elev= 30
       0 2058.06    46.7 2040.09    95.4 2018.72   173.8 1979.47   190.4 1968.14
   217.1 1968.84   237.2 1967.22   330.7 1952.19   877.1 1952.36   963.7 1950.19
  1145.9 1950.47    1166 1947.71  1204.9 1948.34  1242.8  1946.4  1276.2 1948.06
  1309.7 1946.29  1342.2 1947.26 1445.641946.096  1463.3 1941.96  1489.1  1941.9
  1538.3 1942.54 1557.091947.267  1570.3  1950.3  1603.7 1951.66  1620.4 1958.91
  1643.8 1974.95  1717.6 2031.57  1807.3  2090.5  1826.9 2100.88  1852.1 2108.74
#Mann= 6 ,-1 , 0
       0      .1       0   85.01     .06       0  272.09     .05       0
  1119.8      .1       0 1445.64    .045       0 1557.09      .1       0
Bank Sta=1445.64,1557.09
XS Rating Curve= 0 ,0
Exp/Cntr=0.3,0.1

Type RM Length L Ch R = 1 ,51762   ,688.3,699.2,696.2
XS GIS Cut Line= 4
2199697.98294476337440.5214046242199040.72691722 337642.51256663
2198548.42252342337799.0989157952197037.39132686338500.546409731
#Sta/Elev= 30
       0 1998.86    32.3 1983.72    52.9 1969.31   121.7 1964.93   245.1 1965.66
   269.1 1960.74     337 1963.53   701.6 1957.54  1025.3 1955.72  1083.2 1957.21
  1377.9 1951.34  1902.1 1947.66  2014.5 1949.22  2065.2    1946  2177.3 1947.27
  2217.1  1943.8  2267.7 1947.51  2307.6 1942.98  2340.1 1946.58  2354.5 1945.15
  2408.8 1947.03  2423.2  1944.8    2441 1941.01  2502.8 1941.03  2513.7  1946.3
  2535.4 1962.92  2581.8 2004.88    2752  2134.5  2806.5 2171.84  2870.1  2207.6
#Mann= 10 ,-1 , 0
       0      .1       0   213.4     .06       0  336.13     .05       0
  555.93     .06       0     736     .05       0 1135.87     .06       0
 1235.84     .05       0 2202.61      .1       0  2423.2    .045       0
  2513.7      .1       0
Bank Sta=2423.2,2513.7
XS Rating Curve= 0 ,0
Exp/Cntr=0.3,0.1

Type RM Length L Ch R = 1 ,51063   ,1220.9,1199.5,1168
XS GIS Cut Line= 2
2198653.65411264337171.9179104722196870.32073705337888.584784225
#Sta/Elev= 30
       0  1998.2    86.3 1995.94   138.5 1991.71   180.7 1982.59   206.6 1973.83
   226.6 1964.59   254.9 1965.44   378.1 1952.42   979.8 1945.94  1216.7 1945.31
  1255.8 1946.89 1305.361944.726  1319.2 1940.07  1389.9 1939.92 1403.75 1944.62
  1434.9 1946.34  1576.2 1944.01  1598.9 1955.01  1616.2 1970.68  1631.6 1980.82
  1676.3 2001.98  1729.4 2030.34  1767.8  2054.2  1803.6 2072.08  1814.2 2074.93
  1824.8 2074.02  1835.9 2070.89  1878.8 2051.99  1888.5 2055.36  1921.9 2073.65
#Mann= 6 ,-1 , 0
       0     .05       0  129.12    .055       0  246.49     .05       0
  1177.6      .1       0 1305.36    .045       0 1403.75      .1       0
Bank Sta=1305.36,1403.75
XS Rating Curve= 0 ,0
Exp/Cntr=0.3,0.1

Type RM Length L Ch R = 1 ,49863   ,1137.5,1167.9,1186.2
XS GIS Cut Line= 2
2197703.65404414335676.0846160652196157.82084972 337409.41809164
#Sta/Elev= 30
       0 2057.05   104.4 2018.83   273.7 1995.63   293.5 1990.64   302.7 1985.67
   328.6 1980.94   359.3 1961.55   388.7 1962.13   403.3 1954.74   441.3 1948.82
     556 1946.21  1006.8 1946.63  1072.3 1944.43  1418.1 1946.26  1555.2 1943.25
  1594.8 1945.47  1656.2 1940.02  1686.9 1942.25  1750.4 1938.64 1797.661940.043
  1831.4 1938.07 1859.981940.752  1885.2 1941.23  1906.7 1945.83  1924.3 1961.99
  1933.9 1966.72  2012.2 1998.73  2091.4 2023.62  2121.5 2035.61  2322.5 2140.03
#Mann= 8 ,-1 , 0
       0      .1       0  100.17      .1       0  305.96    .055       0
   407.3     .06       0  433.88     .05       0 1485.56      .1       0
 1797.66    .045       0 1859.98      .1       0
Bank Sta=1797.66,1859.98
XS Rating Curve= 0 ,0
Exp/Cntr=0.3,0.1

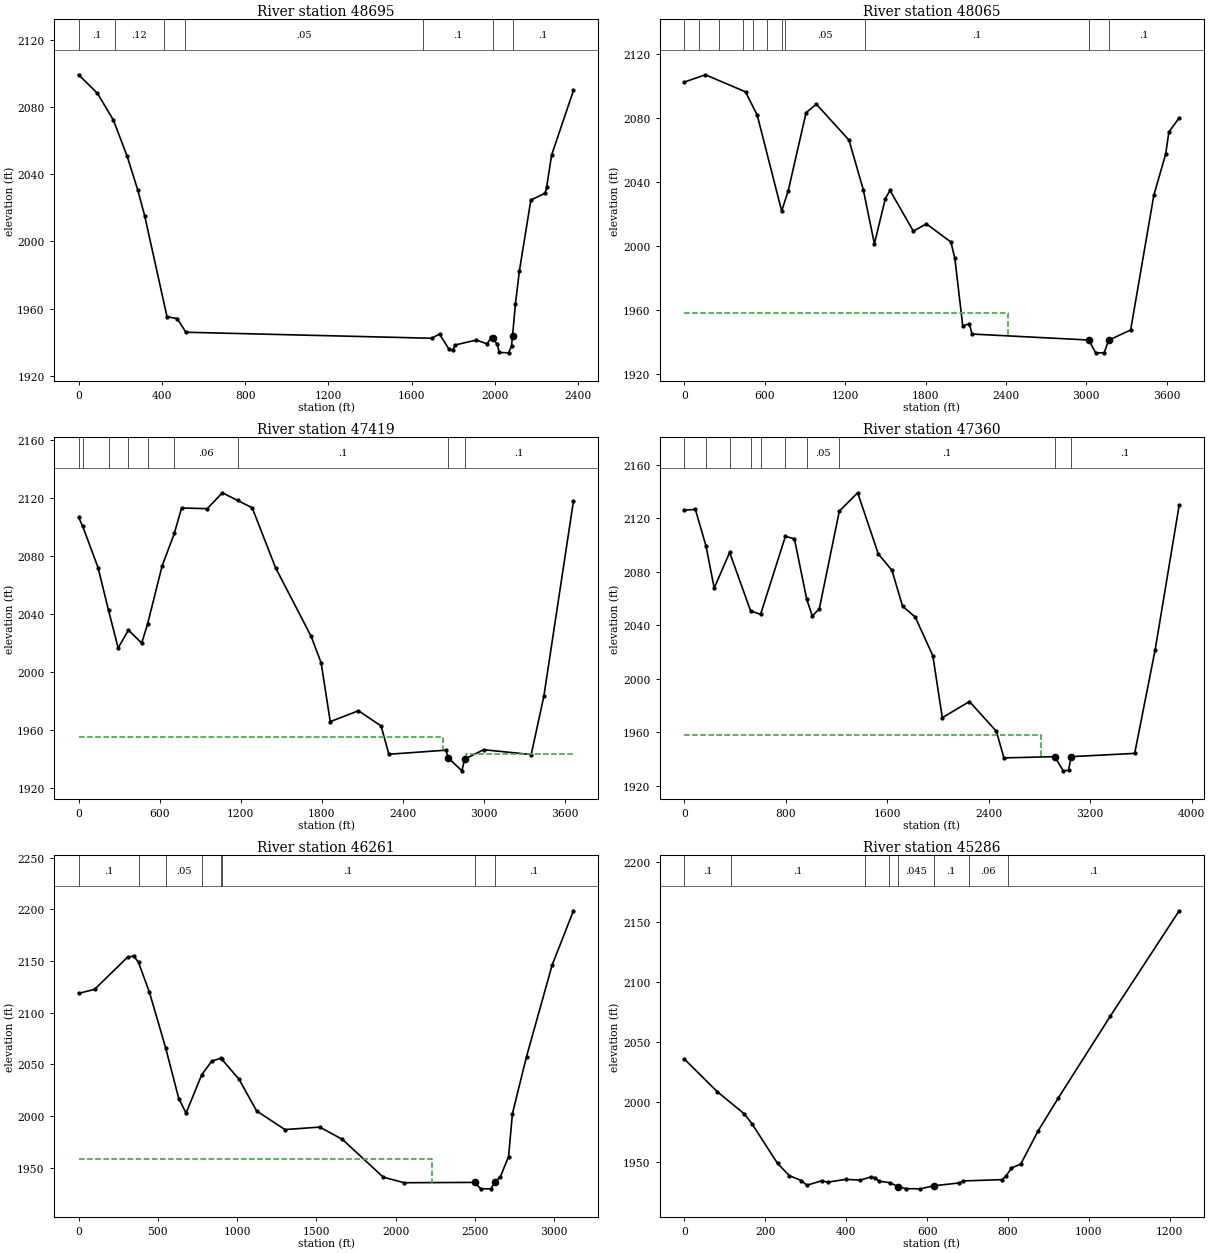
Type RM Length L Ch R = 1 ,48695   ,637.4,630.3,619.9
XS GIS Cut Line= 3
2197649.48748581335559.4178546372195878.65408522 336188.58457531
2195403.65405098336338.584603399
#Sta/Elev= 30
       0 2099.38    90.6 2088.34   167.2 2072.35   233.4 2050.78   284.8 2030.46
   317.2 2015.43   424.7 1955.16   473.5 1954.03   515.4 1945.89  1695.7 1942.31
    1734 1944.79  1779.3 1935.79  1796.6 1935.22  1810.6 1938.33  1910.1 1941.22
  1962.8 1938.97  1983.1 1943.06  1990.71942.261    2011 1938.66  2021.3 1933.83
    2066 1933.61  2079.8 1937.73 2084.731943.679  2098.4 1962.54  2117.6 1982.42
  2172.7  2024.7  2241.5 2028.79  2248.4  2032.2  2272.4 2051.53  2377.4 2090.02
#Mann= 7 ,-1 , 0
       0      .1       0  176.32     .12       0  408.09     .06       0
  509.06     .05       0 1653.43      .1       0  1990.7    .045       0
 2084.73      .1       0
Bank Sta=1990.7,2084.73
XS Rating Curve= 0 ,0
Exp/Cntr=0.3,0.1

Type RM Length L Ch R = 1 ,48065   ,665.7,645.9,631.8
XS GIS Cut Line= 3
2198532.55284668334578.7142944842195908.87384105335503.913372472
2195061.98741147 335838.58461915
#Sta/Elev= 30
       0  2102.7   157.2 2107.26   456.6 2096.58   543.7 2082.08   726.3 2021.99
   775.2  2034.6   908.6 2083.59   985.2 2088.86  1228.7 2066.38  1335.9 2035.14
  1418.2  2001.5    1500 2029.77  1534.8  2034.9  1708.8  2009.4  1806.2 2013.96
  1989.1 2002.57  2018.4 1992.46  2077.5 1950.14  2126.2 1951.35  2147.1 1944.98
  3016.6 1941.25    3019 1941.06  3069.4 1933.22    3133 1933.25  3165.6 1941.08
  3330.5 1947.54  3503.4 2031.89  3591.6 2057.61  3615.7  2071.4  3692.6 2080.29
#Mann= 12 ,-1 , 0
       0      .1       0   110.8     .12       0   261.1      .1       0
   434.1    .055       0     515    .035       0   620.1     .05       0
   731.4     .06       0   753.4     .05       0  1349.9      .1       0
  3016.6      .1       0    3019    .045       0  3165.6      .1       0
#XS Ineff= 2 , 0
         2417.66 1958.44
Permanent Ineff=
       F       F
Bank Sta=3019,3165.6
XS Rating Curve= 0 ,0
Exp/Cntr=0.5,0.3

Type RM Length L Ch R = 1 ,47419   ,57.3,58.7,59.4
XS GIS Cut Line= 4
2197269.97353827 332992.515022342195444.56538647334973.510561898
2195289.00992331 335092.95487681 2194727.8988408335623.510246143
#Sta/Elev= 30
       0 2106.46    30.7 2100.18   144.1 2071.72   221.7 2042.18   292.7 2016.33
   368.9 2028.66   466.8 2019.65   510.1 2032.72   617.7  2072.8   708.6  2095.4
   761.8 2112.89   952.1 2112.41  1063.5 2123.38  1177.3 2118.06  1284.7 2113.02
  1457.5 2071.66  1720.6 2024.36  1794.9 2006.01  1862.2 1965.46  2071.2 1972.99
  2238.5 1962.48  2296.2 1942.98  2718.5 1945.77  2735.5  1940.5  2836.2 1931.52
  2857.2 1939.62  2997.2 1946.09  3349.5 1942.78  3443.3 1983.19  3662.1 2117.72
#Mann= 9 ,-1 , 0
       0     .05       0    30.7    .055       0   221.7      .1       0
   368.9    .055       0   510.1    .035       0   708.6     .06       0
  1177.3      .1       0  2735.5    .045       0  2857.2      .1       0
#XS Ineff= 3 ,-1
       0    2700    1955    2700    2725  1943.4    2867    3800  1943.4
Permanent Ineff=
       F       F       F
Bank Sta=2735.5,2857.2
XS Rating Curve= 0 ,0
Exp/Cntr=0.5,0.3

Type RM Length L Ch R = 1 ,47360   ,1163.7,1099.2,1058.2
XS GIS Cut Line= 5
 2197053.2606459332578.5130693192196189.18572802334044.851985732
2195405.67635664334931.843650475 2195264.0099733335037.399213642
2194650.12078114335609.621494398
#Sta/Elev= 30
       0 2126.13    87.1 2126.73   170.9  2099.4   235.6 2067.91   357.3 2094.54
   522.8 2050.83   601.2 2048.32   796.8 2106.57   867.9  2104.8   964.8 2059.62
  1008.7 2047.11  1064.3 2052.42  1221.9 2125.44  1366.7 2139.15  1529.1 2093.46
    1637 2081.18  1720.3 2054.43  1820.6 2046.23  1959.3 2017.36  2033.7 1971.03
  2247.9 1983.14  2459.8 1960.93  2519.8 1941.01  2919.9 1941.94  2987.5 1931.34
  3029.1 1931.76  3049.6 1941.94  3550.4 1944.39  3712.2 2021.94  3901.4  2129.9
#Mann= 10 ,-1 , 0
       0    .055       0   170.9      .1       0   357.3    .055       0
   522.8    .035       0   601.2     .06       0   796.8    .055       0
   964.8     .05       0  1221.9      .1       0  2919.9    .045       0
  3049.6      .1       0
#XS Ineff= 2 , 0
          2815.6 1957.95
Permanent Ineff=
       F       F
Bank Sta=2919.9,3049.6
XS Rating Curve= 0 ,0
Exp/Cntr=0.5,0.3

Type RM Length L Ch R = 1 ,46261   ,987.1,975,968.5
XS GIS Cut Line= 2
2194578.70284723332182.5859838022194244.98510847335287.246811062
#Sta/Elev= 30
       0 2118.53   100.8 2122.46   308.7 2153.54   348.3 2154.68     378 2148.53
   447.3 2119.47   549.1 2065.92   632.1 2016.69   678.3 2002.74   776.5 2039.67
     840 2052.99   896.1 2055.69   902.7 2055.01  1011.6 2035.56  1123.8  2004.7
  1301.9 1986.74  1521.3 1989.15  1664.9 1977.19  1922.3 1940.68  2054.3  1935.3
  2498.6 1935.61  2537.3 1929.44    2602 1929.38 2627.811936.297  2661.4 1941.02
  2713.1 1960.63  2737.3 2002.16  2826.4 2057.43  2988.1 2146.09  3122.5  2198.5
#Mann= 8 ,-1 , 0
       0      .1       0     378      .1       0   549.1     .05       0
   776.5     .06       0   896.1      .1       0   902.7      .1       0
  2498.6    .045       0 2627.81      .1       0
#XS Ineff= 2 , 0
         2227.84 1958.11
Permanent Ineff=
       F       F
Bank Sta=2498.6,2627.81
XS Rating Curve= 0 ,0
Exp/Cntr=0.3,0.1

Type RM Length L Ch R = 1 ,45286   ,604,566.8,538.8
XS GIS Cut Line= 2
2193267.20720838334042.8024495542193417.20723647  335256.6910979
#Sta/Elev= 30
       0 2035.66    81.2 2008.44   147.9  1989.9   167.2 1981.59   230.3 1948.45
   259.7 1938.19   289.5 1934.06   302.7 1930.18   339.1 1933.87   355.6  1932.8
   398.6 1935.08   434.9  1934.5   461.4 1937.16   471.3 1936.47   481.2 1933.57
   507.7 1932.33  527.941929.115   547.3 1927.35   583.3 1927.19  616.481929.737
   679.6 1932.13   689.5 1933.81   785.3 1934.86   795.3 1937.92   808.5 1944.57
   831.6 1947.96   874.6 1975.72   924.6 2003.23  1053.1 2071.59  1223.1 2159.51
#Mann= 8 ,-1 , 0
       0      .1       0   114.9      .1       0  446.33     .06       0
  506.45      .1       0  527.94    .045       0  616.48      .1       0
  702.65     .06       0  800.22      .1       0
Bank Sta=527.94,616.48
XS Rating Curve= 0 ,0
Exp/Cntr=0.3,0.1

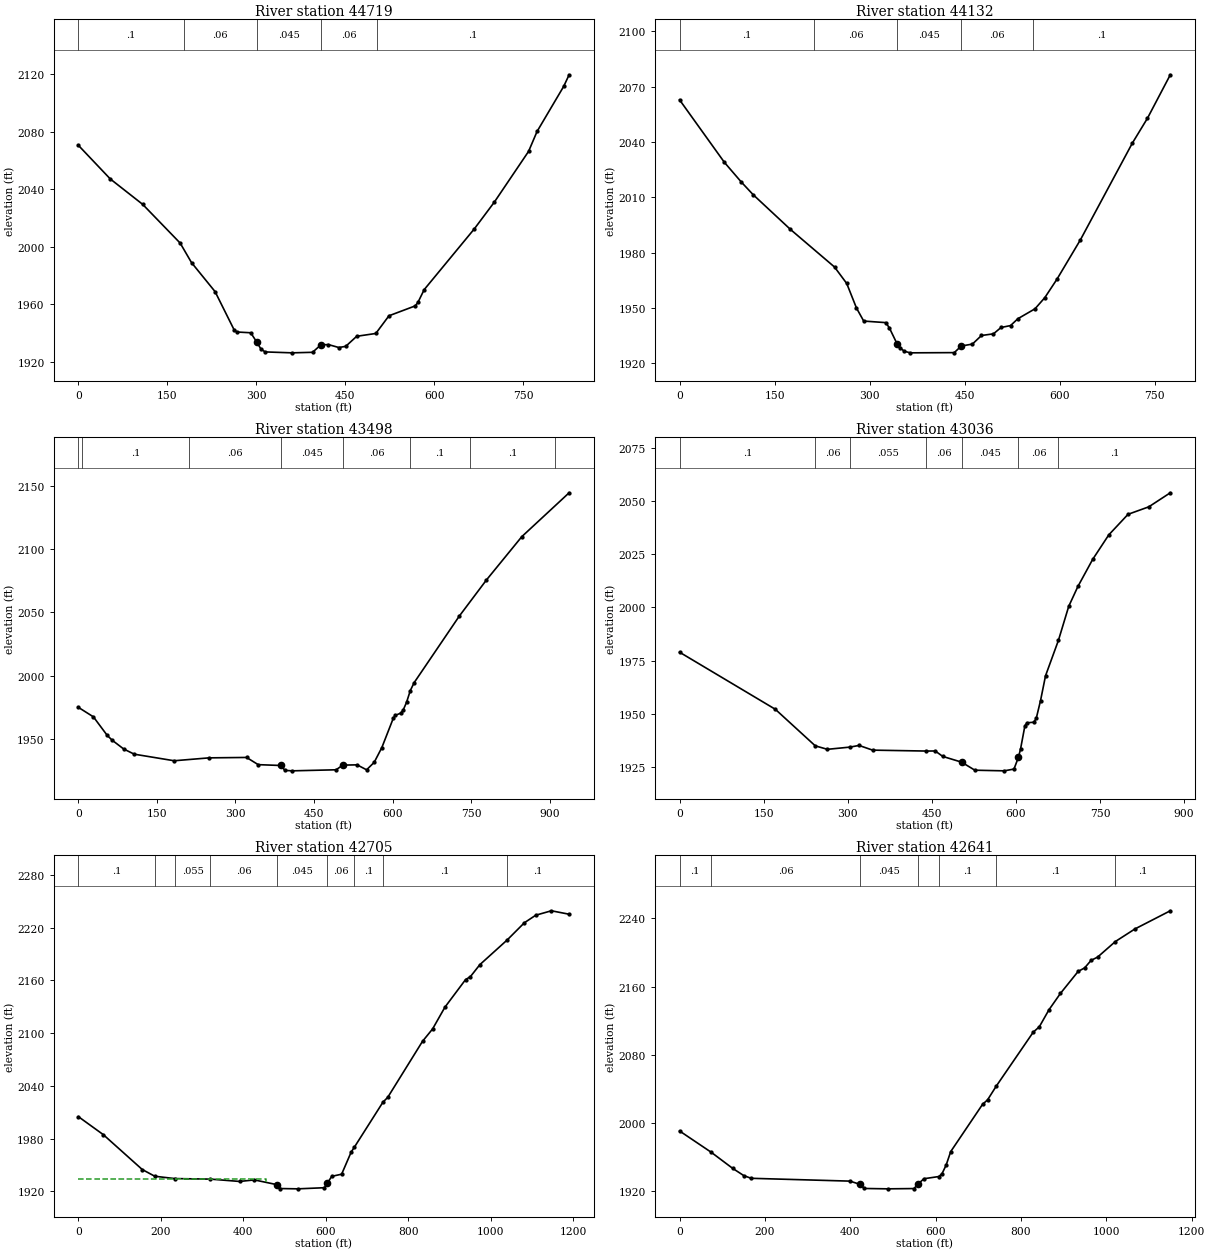
Type RM Length L Ch R = 1 ,44719   ,597.8,587.8,578.3
XS GIS Cut Line= 2
2192636.65171097334690.0245803152193247.76269346335248.357781231
#Sta/Elev= 30
       0 2070.45    53.8 2047.06   108.4  2029.4   171.7 2002.43   190.8 1988.87
   230.6 1968.65   262.8 1941.98   267.5 1940.56   290.7 1940.04  301.011933.478
   307.8 1928.78     315 1926.71   360.4 1926.07     395 1926.44  408.971931.609
   421.7 1931.82   439.3 1929.78   450.9 1930.58   469.5 1937.59   501.7 1939.55
   523.9 1951.86   568.3 1958.75   572.8  1961.2   583.3 1970.04   667.8 2012.29
   701.7 2030.98   759.4 2066.24   773.7 2080.09   818.6 2111.44   827.8 2119.55
#Mann= 5 ,-1 , 0
       0      .1       0  177.74     .06       0  301.01    .045       0
  408.97     .06       0  502.91      .1       0
Bank Sta=301.01,408.97
XS Rating Curve= 0 ,0
Exp/Cntr=0.3,0.1

Type RM Length L Ch R = 1 ,44132   ,641.8,633.6,628.8
XS GIS Cut Line= 2
2192228.31821005335203.9133163092192886.65153906335612.246817231
#Sta/Elev= 30
       0 2062.83    70.8 2028.93    97.7 2018.19   116.1 2011.44   175.1 1992.57
   244.6 1972.22   263.9 1963.29   279.3 1949.96   290.7 1942.91   325.6 1942.07
   331.2 1939.21  343.221930.671   347.9 1928.41     355 1926.52   364.3 1925.69
   433.7 1925.81  444.551929.371   462.3 1930.44   476.6 1935.09   495.5 1935.99
   507.5 1939.43   522.5 1940.47   534.1 1944.19   561.1 1949.56   576.6 1955.61
   595.9 1965.67   632.8 1986.95   714.8 2039.39   738.6 2052.83   774.7 2076.42
#Mann= 5 ,-1 , 0
       0      .1       0  212.59     .06       0  343.22    .045       0
  444.55     .06       0  557.89      .1       0
Bank Sta=343.22,444.55
XS Rating Curve= 0 ,0
Exp/Cntr=0.3,0.1

Type RM Length L Ch R = 1 ,43498   ,448.3,462,471.8
XS GIS Cut Line= 3
2191847.76286881335745.5802119822192139.42928022335909.468991816
2192683.87372939336167.802464649
#Sta/Elev= 30
       0 1974.98    28.7 1967.48    55.2 1952.76    64.8 1948.93    86.5 1942.09
   106.7 1937.98   182.9 1932.79   249.7 1935.08   321.2  1935.4   343.4 1929.71
  386.961929.042   394.3 1925.19   408.1 1924.82   492.2 1925.65  504.86 1929.35
   532.3 1929.55   550.4 1925.63   564.9 1931.52   579.5 1943.17   601.3 1966.27
   604.9 1968.56   615.8  1970.5   620.4 1972.96   626.7 1978.95   633.9 1988.26
   641.2  1994.5   727.3 2047.03   779.2 2075.61   846.9 2109.93   937.2 2144.57
#Mann= 8 ,-1 , 0
       0      .1       0    7.19      .1       0  210.41     .06       0
  386.96    .045       0  504.86     .06       0  633.69      .1       0
  748.34      .1       0  910.34      .1       0
Bank Sta=386.96,504.86
XS Rating Curve= 0 ,0
Exp/Cntr=0.3,0.1

Type RM Length L Ch R = 1 ,43036   ,339.2,331.2,322.8
XS GIS Cut Line= 3
2191575.54064421336037.2466233972191997.76289688336340.024561137
2192275.87651388336562.195704728
#Sta/Elev= 30
       0 1978.92   170.8 1952.05   242.1 1934.83   263.7 1933.19   304.1 1934.24
   320.2 1935.02   344.4 1932.81   439.6 1932.38   456.1 1932.41   469.6 1929.84
  503.221927.147   526.8 1923.36   579.3 1923.06   596.6  1923.9  604.471929.363
   608.3 1933.29   616.1 1944.29   619.9 1945.69   631.9 1945.94   636.3 1947.71
     644 1956.15   652.9 1967.82   675.9 1984.49   694.3 2000.53   710.7  2009.9
     737 2022.62   765.7 2034.15   800.1 2043.85   837.1 2047.37   875.5 2053.99
#Mann= 7 ,-1 , 0
       0      .1       0   242.1     .06       0   304.1    .055       0
   439.6     .06       0  503.22    .045       0  604.47     .06       0
   675.9      .1       0
Bank Sta=503.22,604.47
XS Rating Curve= 0 ,0
Exp/Cntr=0.5,0.3

Type RM Length L Ch R = 1 ,42705   ,66.8,63.6,66.2
XS GIS Cut Line= 4
2191355.67658263336315.1771698892191786.23215197336601.288146228
2191883.45439847336656.8438093962192361.23198622336951.288102388
#Sta/Elev= 30
       0    2005    60.4 1984.56   154.9  1944.9   185.2 1937.27   233.7 1934.62
   320.1    1934   391.1 1931.35   426.7  1933.1  480.961927.748   489.8 1923.28
   532.4 1922.95   596.7 1924.23  603.331929.046   614.4 1937.15   638.4  1939.6
   661.5 1964.69   669.3 1970.33   738.6 2021.46   750.2 2026.94   834.6 2090.67
   859.1 2104.77   888.9 2129.44     939 2160.82   950.6  2164.1   973.7 2177.82
  1039.7 2205.75  1081.6 2225.42  1109.2 2233.99  1147.1 2239.02  1190.1  2235.1
#Mann= 9 ,-1 , 0
       0      .1       0   185.2     .06       0   233.7    .055       0
   320.1     .06       0  480.96    .045       0  603.33     .06       0
   669.3      .1       0   738.6      .1       0  1039.7      .1       0
#XS Ineff= 2 , 0
             454  1933.8     629          1933.8
Permanent Ineff=
       F       F
Bank Sta=480.96,603.33
XS Rating Curve= 0 ,0
Exp/Cntr=0.5,0.3

Type RM Length L Ch R = 1 ,42641   ,900.4,930.3,955.8
XS GIS Cut Line= 5
2191333.45418614336415.1769699012191697.34322214336617.954779565
2191855.67656688336717.9549076412192294.56545289336973.510498896
2192328.38493906336991.079689473
#Sta/Elev= 30
       0 1990.76    73.7 1965.97   124.4 1946.94   150.6 1938.41   167.8 1935.29
   399.3 1931.98  423.03 1928.16   432.9 1923.37   487.2 1922.94   549.2 1923.27
  558.641928.525   572.5 1934.78   607.4 1937.35     615 1940.77   624.6 1950.79
   635.3 1966.58   709.9 2021.95   721.7 2027.28   741.9 2043.24   828.8 2106.66
   842.8 2112.77   865.5 2132.79   892.4 2151.99   933.9 2177.77   949.1 2181.89
   964.2 2190.71   979.4 2194.52  1021.2 2212.82  1066.8 2227.49  1149.8 2248.83
#Mann= 7 ,-1 , 0
       0      .1       0    73.7     .06       0  423.03    .045       0
  558.64     .06       0   607.4      .1       0   741.9      .1       0
  1021.2      .1       0
Bank Sta=423.03,558.64
XS Rating Curve= 0 ,0
Exp/Cntr=0.5,0.3

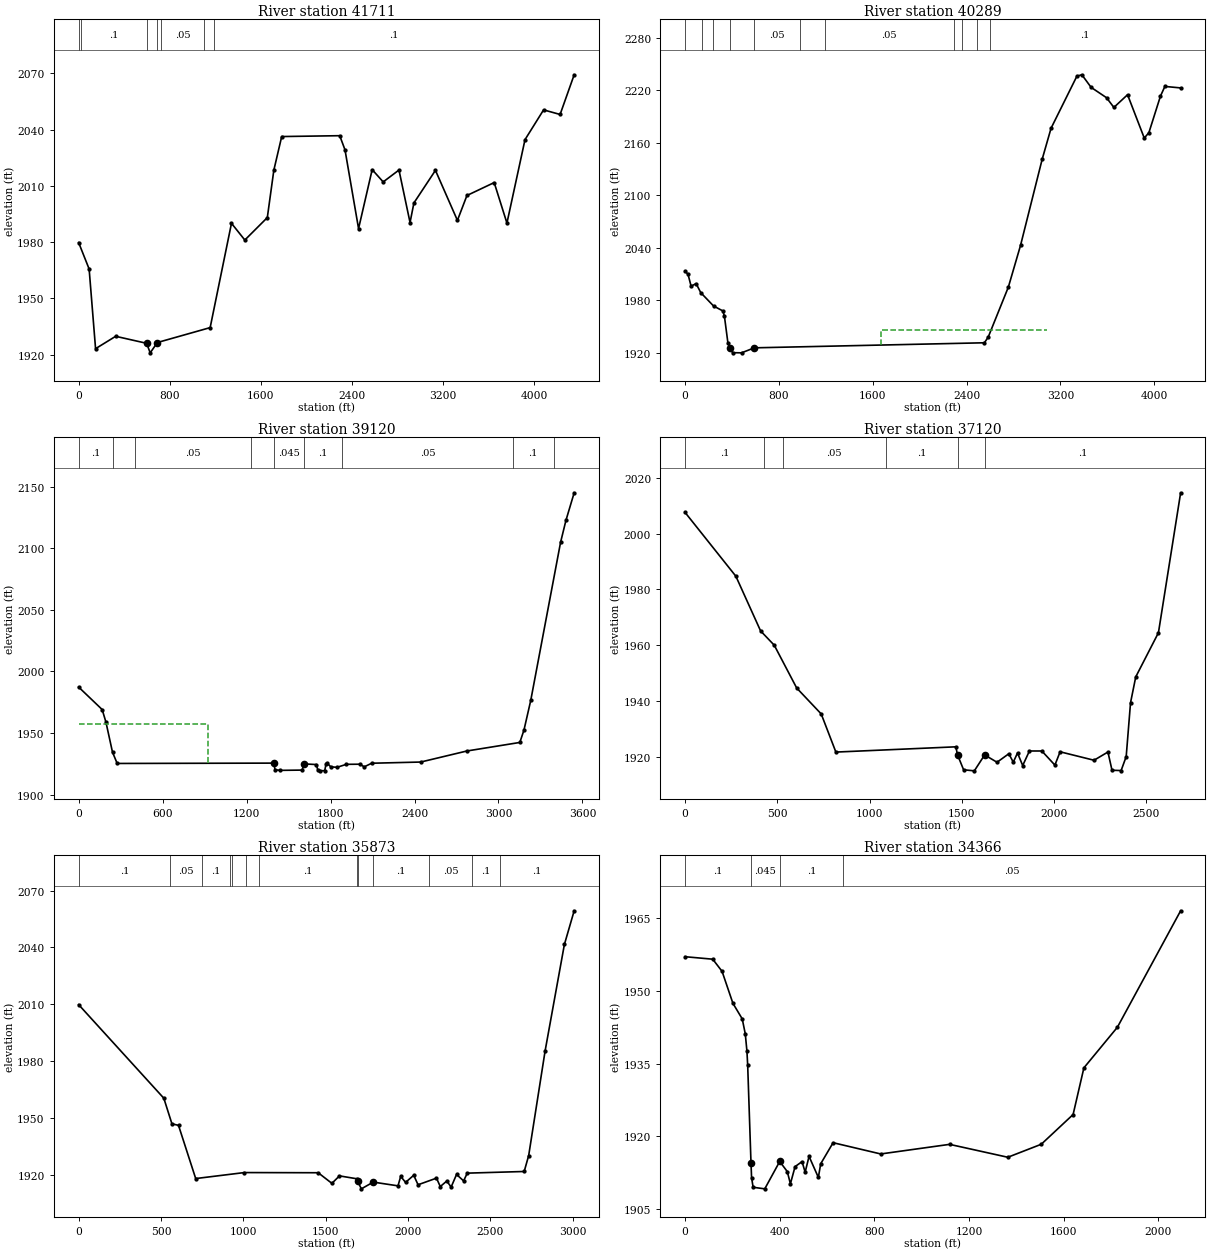
Type RM Length L Ch R = 1 ,41711   ,1412,1422.3,1409.1
XS GIS Cut Line= 4
2190883.87372047 336734.46898222 2191092.2072933337262.246798053
 2191624.6723044338253.5590887692192861.14586369340604.388362673
#Sta/Elev= 30
       0 1979.78    92.2 1965.67   148.6 1923.19     325 1929.79  596.861926.054
     628 1920.97  690.891926.469  1154.2 1934.42  1341.4 1990.04  1458.5 1981.12
  1655.9 1993.09  1713.2  2018.4  1782.1  2036.3  2291.4 2036.76  2337.6 2029.21
  2456.6 1987.23  2576.1 2018.66  2672.8 2012.11  2811.3 2018.45  2908.4 1990.47
  2942.4  2000.9  3131.4 2018.28  3324.2  1991.6  3407.7 2004.87  3646.9 2011.76
  3758.7 1990.16  3917.3 2034.65  4080.4 2050.52  4225.3 2048.08  4348.8 2069.24
#Mann= 7 ,-1 , 0
       0     .06       0   19.72      .1       0  596.86    .045       0
  690.89    .055       0  726.54     .05       0 1099.37     .06       0
 1186.35      .1       0
Bank Sta=596.86,690.89
XS Rating Curve= 0 ,0
Exp/Cntr=0.3,0.1

Type RM Length L Ch R = 1 ,40289   ,1140.4,1168.9,1181.2
XS GIS Cut Line= 4
2189723.09848297336739.973564386 2189934.2096093338412.195613638
2189996.10936229339550.2347962332190054.90462519340948.949883126
#Sta/Elev= 30
       0 2013.31    24.7 2009.88    51.1 1996.32    94.1 1999.17   133.8 1988.81
   242.9  1973.6   322.3 1967.97   335.5 1961.73   365.3 1931.22  386.941925.268
     405 1920.34     481 1920.16  590.251925.876  2552.2 1931.64    2585 1938.28
  2756.3  1995.2  2860.1 2042.79  3044.6  2141.1  3120.4 2176.51  3340.8 2235.97
  3383.1  2237.5  3461.9 2223.13  3593.3 2211.33    3656 2200.23  3772.6 2214.74
  3915.1 2165.27  3954.5 2171.45    4053 2213.09  4090.8 2224.21  4225.2  2222.5
#Mann= 11 ,-1 , 0
       0     .06       0  142.92      .1       0  240.47      .1       0
  386.94    .045       0  590.25     .05       0  978.38      .1       0
 1189.27     .05       0 2293.35    .045       0 2363.37     .07       0
 2485.76     .05       0 2597.49      .1       0
#XS Ineff= 1 ,-1
  1667.8  3081.5 1946.36
Permanent Ineff=
       F
Bank Sta=386.94,590.25
XS Rating Curve= 0 ,0
Exp/Cntr=0.3,0.1

Type RM Length L Ch R = 1 ,39120   ,1894.9,1999.5,2034.2
XS GIS Cut Line= 3
2188889.76517589335845.5291590542188661.81714097336900.709463388
2188500.87618989339356.640247062
#Sta/Elev= 30
       0 1987.26   168.1 1969.02     195 1958.85     242  1934.4   275.5 1925.26
 1394.131925.541  1403.3 1920.16  1439.5 1919.66  1597.3 1919.88 1610.431924.912
  1699.2 1924.37  1708.9 1919.83  1725.5 1919.27  1758.4 1919.48  1768.2 1924.91
  1774.8 1925.63  1801.1 1922.56  1846.2 1922.12  1912.9 1924.56  2008.5 1924.65
  2041.1 1922.53  2093.7 1925.44  2444.3 1926.41  2774.3 1935.38  3152.4 1942.31
    3182 1952.37  3230.4 1976.41  3443.5 2104.71  3482.2 2122.67  3540.7 2144.94
#Mann= 9 ,-1 , 0
       0      .1       0  242.53      .1       0  404.58     .05       0
 1233.33      .1       0 1394.13    .045       0 1610.43      .1       0
 1883.75     .05       0 3103.18      .1       0 3393.01      .1       0
#XS Ineff= 2 , 0
          921.34 1957.16
Permanent Ineff=
       F       F
Bank Sta=1394.13,1610.43
XS Rating Curve= 0 ,0
Exp/Cntr=0.3,0.1

Type RM Length L Ch R = 1 ,37120   ,1266.1,1247.3,1162.7
XS GIS Cut Line= 3
2188586.02860711335555.9028638232187467.54295473336439.973508224
2186561.98735113337317.751280233
#Sta/Elev= 30
       0 2007.55   275.3 1984.74   409.4 1965.18   483.4 1960.07   605.1 1944.76
     738 1935.49   817.5 1921.85  1467.7 1923.73  1477.8 1920.74  1510.1 1915.51
  1568.3 1915.14    1624 1920.83  1691.3 1918.21  1755.2 1921.25  1779.4 1918.23
  1802.3 1921.53  1830.5 1917.03  1866.9 1922.24  1934.3 1922.24    2005 1917.19
  2033.3 1921.95  2217.2 1918.93  2292.6 1921.87  2314.7 1915.35  2364.1 1915.24
  2391.6 1920.24  2415.1 1939.49  2443.4 1948.74  2566.4 1964.53  2686.8 2014.59
#Mann= 6 ,-1 , 0
       0      .1       0  426.53      .1       0  530.06     .05       0
 1086.64      .1       0  1477.8    .045       0    1624      .1       0
Bank Sta=1477.8,1624
XS Rating Curve= 0 ,0
Exp/Cntr=0.3,0.1

Type RM Length L Ch R = 1 ,35873   ,1490,1507.3,1466.7
XS GIS Cut Line= 4
2186542.81337155334485.5488551272186491.09608872336111.968914896
2186389.39629219337293.3512205612186378.65405639337489.761632586
#Sta/Elev= 30
       0 2009.79   517.4 1960.38   566.6 1946.88   606.6 1946.05     711 1917.97
  1006.5 1921.13  1454.9 1921.04  1538.2 1915.44  1584.2 1919.38  1692.7 1917.81
 1694.211916.584  1717.1 1912.54  1789.41916.093  1939.7 1914.12  1956.1 1919.12
  1985.8 1915.94  2035.2 1919.71  2061.5 1914.69  2173.5 1918.19  2196.5 1913.74
  2236.1 1916.67  2262.4 1913.47  2295.3 1920.14  2338.1 1916.73  2360.4 1920.83
  2706.1  1921.7  2733.3 1930.08  2833.3 1985.42  2950.3 2041.55  3009.7 2059.34
#Mann= 13 ,-1 , 0
       0      .1       0  557.68     .05       0   747.3      .1       0
  918.75     .05       0   932.8      .1       0 1017.92     .05       0
 1096.84      .1       0  1692.7      .1       0 1694.21    .045       0
  1789.4      .1       0 2129.23     .05       0 2389.63      .1       0
 2560.78      .1       0
Bank Sta=1694.21,1789.4
XS Rating Curve= 0 ,0
Exp/Cntr=0.3,0.1

Type RM Length L Ch R = 1 ,34366   ,1188.7,1194.9,1204.3
XS GIS Cut Line= 3
2185363.06848913335348.5147331512185294.23710065337115.997505331
2185276.07563155337441.547373254
#Sta/Elev= 30
       0 1957.04   116.8 1956.53   156.2 1954.03   202.2 1947.43   241.6 1944.22
   254.4 1941.15   261.4 1937.58   264.6 1934.64  278.671914.433     281 1911.51
   287.6 1909.51   336.8 1909.19  399.97 1914.83     432 1912.75   445.2 1910.23
   464.9 1913.77   494.4  1914.8   507.5 1912.62     524 1915.88   563.4 1911.54
   573.2 1914.35   625.7  1918.7     827 1916.38  1118.2 1918.36  1364.3  1915.7
  1505.7 1918.38  1640.3 1924.51  1685.9 1934.13  1827.5  1942.5  2094.9 1966.51
#Mann= 4 ,-1 , 0
       0      .1       0  278.67    .045       0  399.97      .1       0
  668.53     .05       0
Bank Sta=278.67,399.97
XS Rating Curve= 0 ,0
Exp/Cntr=0.3,0.1

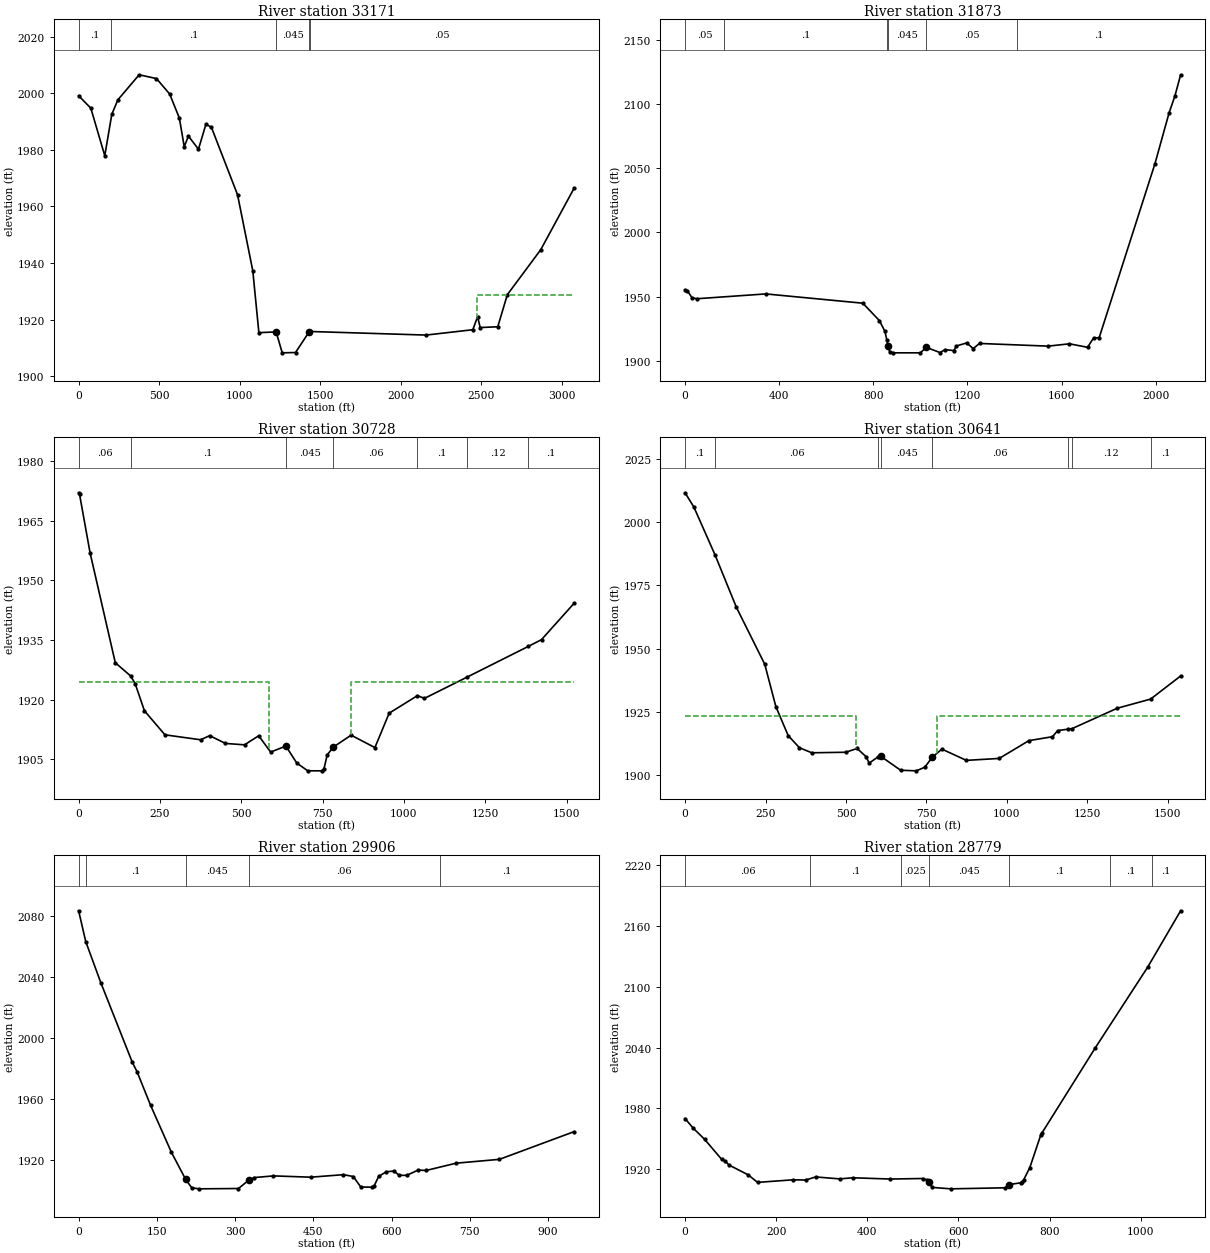
Type RM Length L Ch R = 1 ,33171   ,1267.9,1297.8,1286.4
XS GIS Cut Line= 3
2184687.13399921334523.358452535 2184191.1935363335426.639576897
2184003.69358322337463.098102391
#Sta/Elev= 30
       0 1999.12    75.6 1994.73   162.3 1977.93   205.8 1992.54   243.6 1997.68
   375.6 2006.53   483.2 2005.19   565.5 1999.69   625.4 1991.17   655.3 1981.12
   681.5 1984.86   743.7 1980.22   790.1 1989.07   824.4 1987.93   986.3 1964.12
  1080.9 1937.25  1118.7 1915.39  1225.7 1915.66  1263.6 1908.26    1346 1908.37
  1430.8  1915.7  1433.8 1915.81  2156.5 1914.54  2446.4 1916.43  2476.1    1921
  2492.3  1917.2  2601.3 1917.47  2660.6  1928.8  2868.2 1944.73  3075.5 1966.49
#Mann= 5 ,-1 , 0
       0      .1       0  200.38      .1       0  1225.7    .045       0
  1430.8     .05       0  1433.8     .05       0
#XS Ineff= 2 , 0
                         2470.01         1928.79
Permanent Ineff=
       F       F
Bank Sta=1225.7,1430.8
XS Rating Curve= 0 ,0
Exp/Cntr=0.3,0.1

Type RM Length L Ch R = 1 ,31873   ,1129.8,1144.6,1132.5
XS GIS Cut Line= 4
2183260.88561054334518.2263991012183053.59607397335254.330210224
 2182998.0404108335528.6357639732182706.37399939336549.469024137
#Sta/Elev= 30
       0 1955.14       9 1954.82    29.5 1949.11      50 1948.41   343.1 1952.16
   755.5 1944.93     826 1931.36   849.4 1922.98   857.9 1915.93  863.041911.392
   869.5 1907.11   885.8 1906.29    1000 1906.28  1024.9 1910.57  1083.5  1906.5
  1104.9 1908.77  1142.5 1908.02  1152.7 1911.59  1197.1 1914.02  1224.4 1909.58
  1251.4 1913.59  1543.4  1911.5  1633.8 1913.32  1710.6 1910.57  1736.2 1917.83
  1760.1  1918.1  1997.2  2053.6  2056.9 2092.99  2082.1  2106.4  2106.3  2122.8
#Mann= 6 ,-1 , 0
       0     .05       0   164.6      .1       0   857.9      .1       0
  863.04    .045       0  1024.9     .05       0  1411.9      .1       0
Bank Sta=863.04,1024.9
XS Rating Curve= 0 ,0
Exp/Cntr=0.5,0.3

Type RM Length L Ch R = 1 ,30728   ,88.5,87.2,85.3
XS GIS Cut Line= 6
 2182312.5516243  334895.31583642182125.32922973335150.963947147
2182065.18105605335327.353030056 2182006.1880638335627.538125232
2181956.70883206335887.0868187252182117.54315606336307.242146388
#Sta/Elev= 30
       0 1971.99     2.9 1971.57    35.1 1956.91   112.7 1929.25   159.7 1925.93
   173.8 1923.99   202.2 1917.17   265.3 1911.12   375.1 1909.87   402.8 1910.91
   451.4 1908.95     510  1908.6   553.5 1910.88   590.3 1906.78   637.1 1908.29
   670.5 1904.02   704.3 1902.07   747.4 1902.06   754.1 1902.54   764.1 1906.07
  783.121908.052   837.7 1911.03   910.7 1907.91   954.6 1916.56  1041.4 1920.97
    1063 1920.28  1194.3 1925.64  1382.2 1933.35  1422.9 1935.06  1523.3 1944.22
#Mann= 7 ,-1 , 0
       0     .06       0   159.7      .1       0   637.1    .045       0
  783.12     .06       0  1041.4      .1       0  1194.3     .12       0
  1382.2      .1       0
#XS Ineff= 2 , 0
           584.9  1924.5     838          1924.5
Permanent Ineff=
       F       F
Bank Sta=637.1,783.12
XS Rating Curve= 0 ,0
Exp/Cntr=0.5,0.3

Type RM Length L Ch R = 1 ,30641   ,826.7,735.2,638.7
XS GIS Cut Line= 5
2182129.21800147334861.9825697242181979.21830148335278.649387315
2181922.27386156335628.6493434762181891.71814838335923.093636483
2182072.40413871336331.547543973
#Sta/Elev= 30
       0 2011.49    27.5  2005.8    93.7 1986.79   159.2 1966.38   247.6 1943.85
     282 1927.19   320.4 1915.72   355.2 1910.95   393.6 1908.94   499.1 1909.15
   534.8 1910.64   562.1 1907.44   572.1 1904.89   598.7 1907.22   608.6 1907.51
   669.8 1902.06   718.3 1901.82   744.7 1903.22   768.2 1907.18   798.1 1910.39
     874 1905.95   976.2 1906.71  1068.6 1913.74  1141.7 1915.28    1158  1917.7
    1189 1918.23  1201.4  1918.4  1343.2 1926.52  1446.7 1930.11  1540.1 1939.24
#Mann= 8 ,-1 , 0
       0      .1       0    93.7     .06       0   598.7    .055       0
   608.6    .045       0   768.2     .06       0    1189      .1       0
  1201.4     .12       0  1446.7      .1       0
#XS Ineff= 2 , 0
       0  530.79 1923.44  781.53       0 1923.44
Permanent Ineff=
       F       F
Bank Sta=608.6,768.2
XS Rating Curve= 0 ,0
Exp/Cntr=0.5,0.3

Type RM Length L Ch R = 1 ,29906   ,1008.9,1126.5,1215
XS GIS Cut Line= 4
2181239.07083164335866.2699312272181624.48738363336078.075281888
 2181874.4875398336206.5474658912182061.98749289336338.492083892
#Sta/Elev= 30
       0 2083.28    13.6 2063.11    42.6 2036.04     103 1983.82   111.9  1977.8
   138.1 1955.58   177.9 1924.86  205.231907.084   216.6  1901.7     230 1900.91
   306.5 1901.13  325.761906.485   336.5  1908.3   373.6  1909.4     445 1908.55
   507.7  1910.2   526.6    1909   540.9 1902.13     563    1902   566.7 1902.93
   575.3 1909.07   589.9 1912.11   604.5 1912.57   614.6 1909.81   628.9 1909.74
   650.8  1913.2   666.3 1912.97   723.8 1917.74   806.7 1920.25   950.1 1938.44
#Mann= 5 ,-1 , 0
       0     .06       0   13.49      .1       0  205.23    .045       0
  325.76     .06       0  692.35      .1       0
Bank Sta=205.23,325.76
XS Rating Curve= 0 ,0
Exp/Cntr=0.3,0.1

Type RM Length L Ch R = 1 ,28779   ,571.3,689.6,750.4
XS GIS Cut Line= 3
2180802.95982721336064.1865301432180661.29311581336539.186564401
2180503.79310273337109.730370805
#Sta/Elev= 30
       0 1970.01    17.5 1960.72    42.6 1949.67    80.3 1929.83    87.1 1928.33
    96.6 1924.18   138.5 1914.57     159 1907.14   236.4 1909.66   264.7 1909.48
   286.5  1912.5   339.2 1910.59   368.2 1911.68     450 1910.44   521.8 1910.96
     532  1909.5  534.921907.466   542.2 1902.18   583.4 1900.78   702.2  1901.8
   711.51905.018   736.2 1906.69   739.6 1907.25   742.9 1909.43   756.6 1921.76
   780.4 1953.52   783.8 1956.24   900.2 2039.69  1015.3 2119.28  1087.6 2174.81
#Mann= 7 ,-1 , 0
       0     .06       0  274.18      .1       0  474.02    .025       0
  534.92    .045       0   711.5      .1       0  932.95      .1       0
 1024.29      .1       0
Bank Sta=534.92,711.5
XS Rating Curve= 0 ,0
Exp/Cntr=0.3,0.1