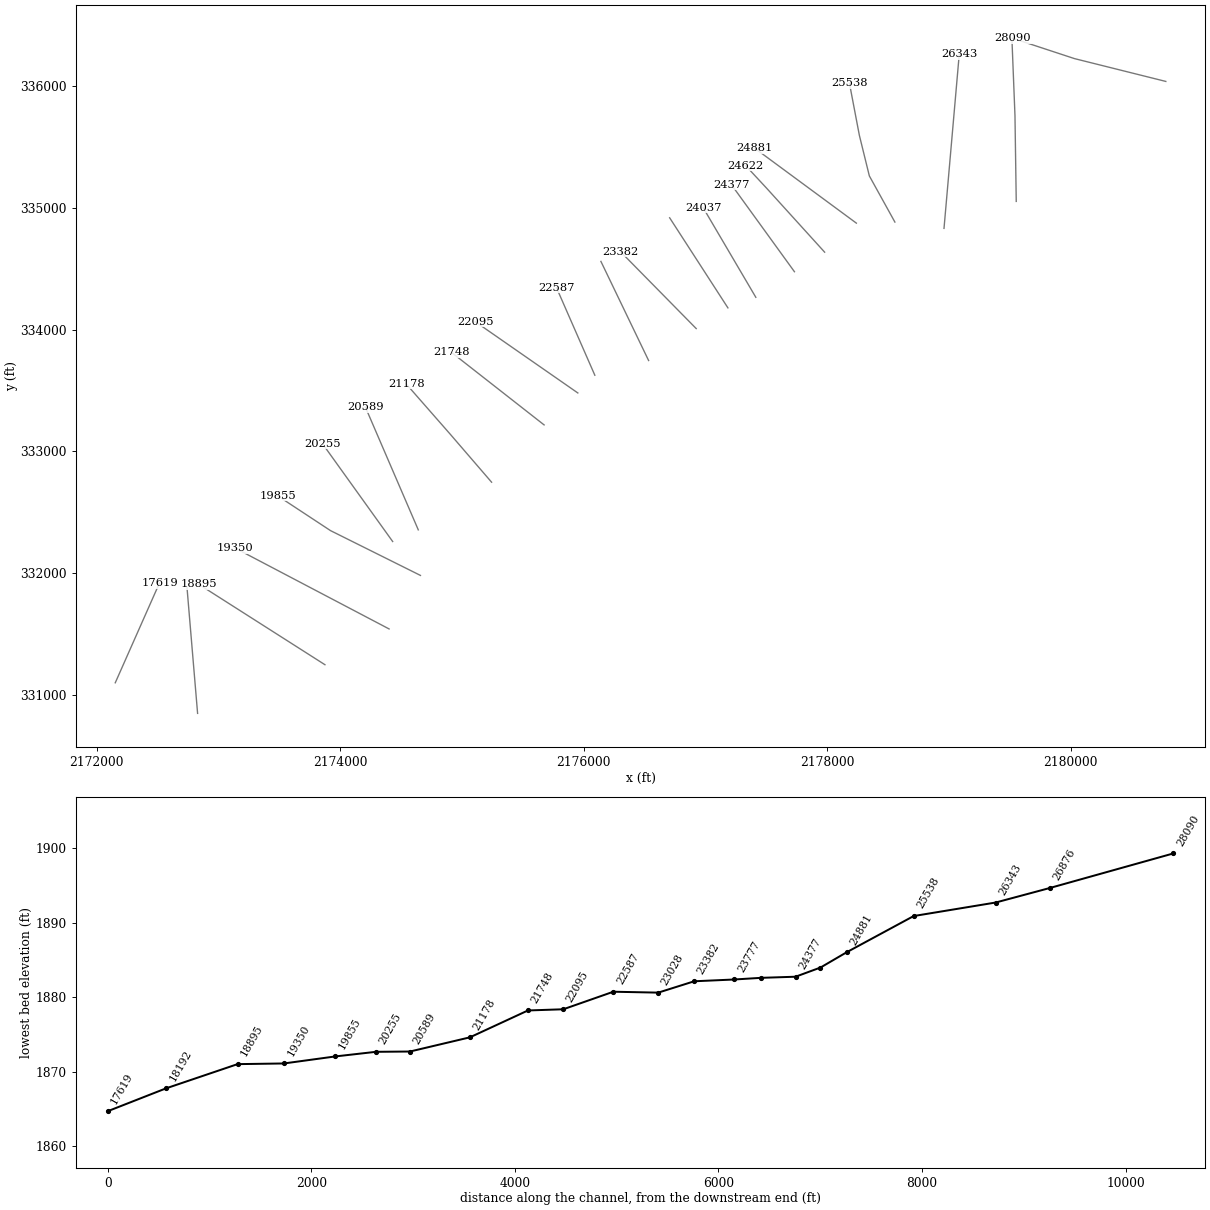
HEC-RAS study ANTHONYCK.prj: ANTHONYCK

--- ANTHONYCK.g01 (geometry) --- (continued)

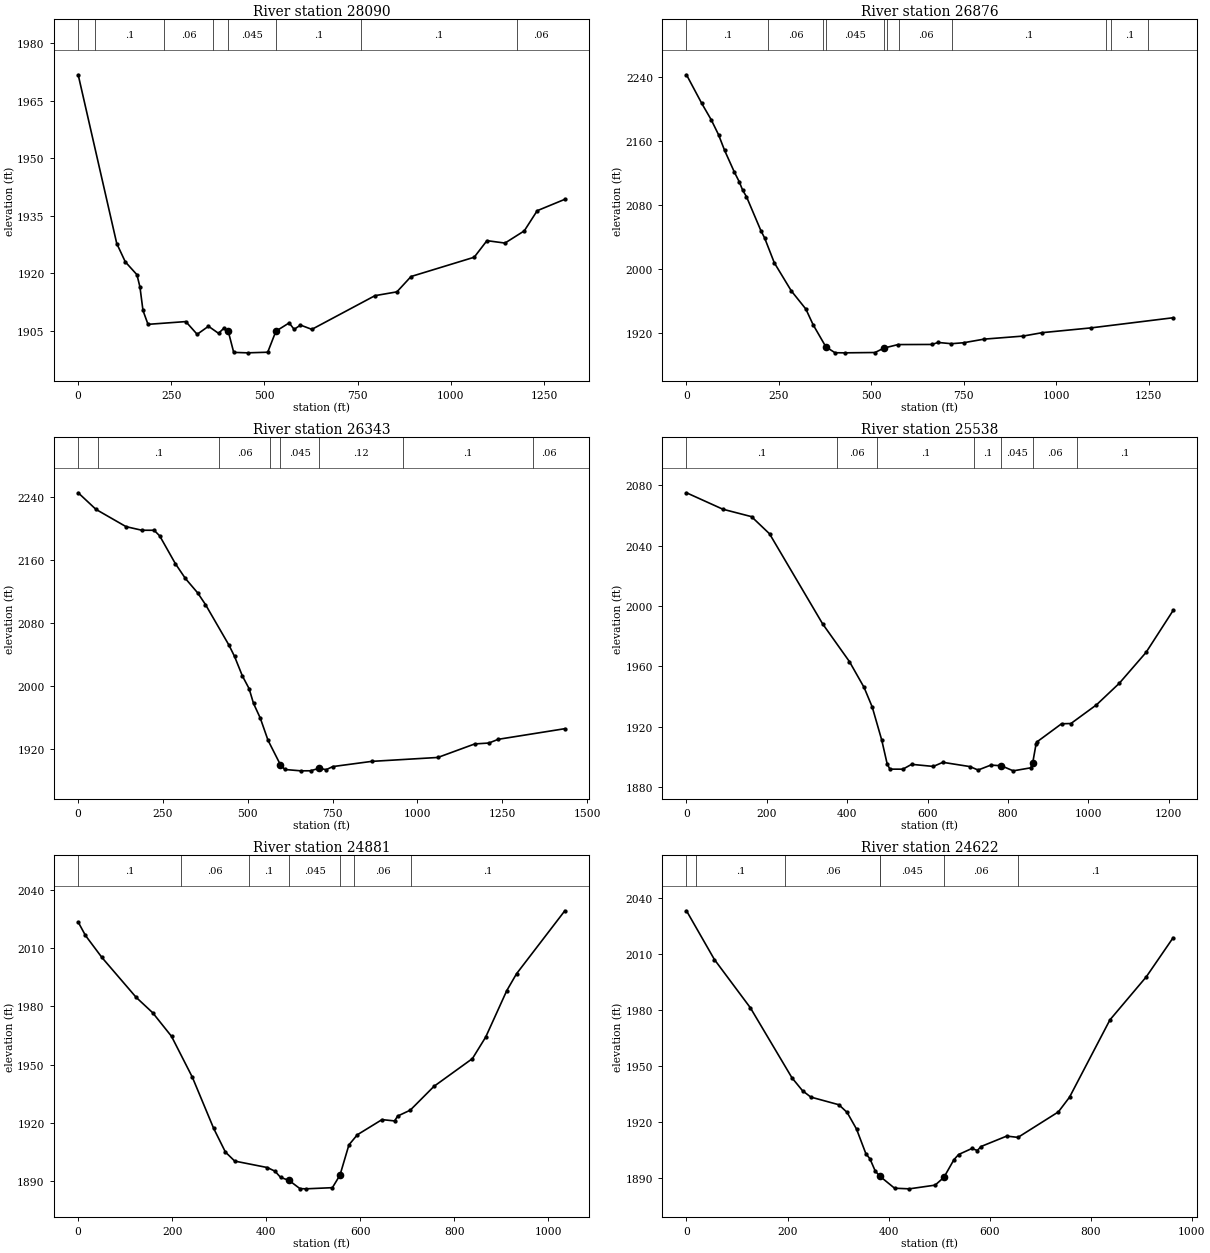
Type RM Length L Ch R = 1 ,28090   ,1287.3,1213.5,1104.5
XS GIS Cut Line= 3
2180780.73743072336039.8808044792180030.73761839336227.381085649
2179524.48731856336394.047747061
#Sta/Elev= 30
       0 1971.76   103.5 1927.76   126.5 1922.98   157.7 1919.63   165.8 1916.41
   173.9 1910.31   187.4 1906.69   288.9 1907.41   319.3 1904.09   349.7 1906.19
   376.8 1904.34   390.3 1905.62  402.921904.831   417.4 1899.38   454.6 1899.26
   508.7 1899.42  530.681904.904   566.2 1907.06   579.7 1905.38   596.6  1906.5
   627.1 1905.38   796.6 1914.17   855.4 1915.16   893.4 1919.16  1062.9 1924.19
  1097.1 1928.51  1145.5 1927.88  1197.3 1931.06    1232 1936.32  1306.1 1939.29
#Mann= 8 ,-1 , 0
       0     .06       0      45      .1       0  230.23     .06       0
  361.88      .1       0  402.92    .045       0  530.68      .1       0
  758.61      .1       0 1176.46     .06       0
Bank Sta=402.92,530.68
XS Rating Curve= 0 ,0
Exp/Cntr=0.3,0.1

Type RM Length L Ch R = 1 ,26876   ,539.1,533.1,528.9
XS GIS Cut Line= 3
2179552.26515014335053.769915804 2179541.8485043335758.631038889
2179517.54310672336369.742021397
#Sta/Elev= 30
       0 2242.56    41.4 2206.66      67 2186.17    86.7 2167.57   103.1 2147.96
   129.3 2120.98   142.5 2108.89   152.3 2097.82   162.2 2090.13   201.5 2047.29
   211.4 2038.35   237.6 2007.27   283.6 1972.12   322.9 1949.45   342.6 1929.79
  377.061902.142   401.7 1894.77   427.8 1894.63     510 1895.05  534.441900.617
   572.3 1904.97   664.2 1905.12   680.6 1907.62   716.7 1906.06   749.5 1907.25
   805.3 1911.79   910.4 1915.59   962.9 1919.91  1094.3 1925.85  1316.5 1938.54
#Mann= 11 ,-1 , 0
       0      .1       0  221.07     .06       0  369.97      .1       0
  377.06    .045       0  534.44      .1       0  542.92      .1       0
  575.38     .06       0  719.08      .1       0 1135.49      .1       0
  1149.7      .1       0 1249.09     .06       0
Bank Sta=377.06,534.44
XS Rating Curve= 0 ,0
Exp/Cntr=0.3,0.1

Type RM Length L Ch R = 1 ,26343   ,791.8,805.3,809.6
XS GIS Cut Line= 2
2178958.98484063334832.2149127272179083.97802897336261.274718642
#Sta/Elev= 30
       0 2245.68    52.5 2224.59   141.1 2202.68   187.6 2198.12   223.8 2198.08
   240.3 2190.95   286.4 2155.75     316 2136.89   352.2 2118.61   375.3 2103.74
   444.6 2052.15   460.9 2037.93     484 2013.18   503.7 1997.15   516.9 1978.21
   536.7 1959.71   559.7 1931.37  596.081900.461   609.1 1894.39   656.6 1892.68
   684.9 1892.75  710.711895.973     731 1894.13   750.5 1898.09   865.5  1904.7
  1060.3 1909.67    1169 1926.84  1210.8 1927.99  1238.1 1932.69  1434.5 1946.18
#Mann= 8 ,-1 , 0
       0      .1       0    59.3      .1       0  414.85     .06       0
  565.12      .1       0  596.08    .045       0  710.71     .12       0
  956.06      .1       0 1342.16     .06       0
Bank Sta=596.08,710.71
XS Rating Curve= 0 ,0
Exp/Cntr=0.3,0.1

Type RM Length L Ch R = 1 ,25538   ,621.4,657,680.2
XS GIS Cut Line= 4
2178555.50566073334884.0753733072178345.78363922335263.242265895
 2178263.8392493335596.5755887332178182.58908372 336023.42742531
#Sta/Elev= 30
       0 2075.09    90.5  2064.2   161.8 2059.28   206.7  2047.9   338.7 1988.29
   405.5 1963.27     442 1946.12   462.3 1933.13   485.9 1911.28   499.4 1895.51
   506.2    1892   538.6 1891.97   560.2 1895.18   614.3 1893.79     638 1896.51
   705.5 1893.68   725.7 1891.41   757.3 1894.66   783.11894.268   813.2 1890.87
   856.6 1892.86   861.5 1895.93   869.8 1908.33   873.3 1910.26   933.4 1922.05
   956.8 1922.22  1020.3 1934.58    1077 1948.84  1143.8 1969.36  1211.1 1997.11
#Mann= 7 ,-1 , 0
       0      .1       0  375.42     .06       0  473.71      .1       0
  715.72      .1       0   783.1    .045       0   861.5     .06       0
  972.38      .1       0
Bank Sta=783.1,861.5
XS Rating Curve= 0 ,0
Exp/Cntr=0.3,0.1

Type RM Length L Ch R = 1 ,24881   ,270.3,258.7,247.9
XS GIS Cut Line= 2
2178239.07059805334875.2791310552177405.73729096335489.862547562
#Sta/Elev= 30
       0 2023.46    15.4 2016.58    50.5 2005.21   123.3 1984.69   158.5 1976.75
   198.6 1964.59   242.9 1943.55   288.3 1917.16   313.3 1904.97   333.1 1900.33
   402.5    1897   418.7 1895.13   430.6 1891.96  448.911890.333   471.7 1886.17
     484 1886.03   540.9 1886.63  557.051893.082   576.1 1908.68     594 1913.88
   646.5 1921.69   673.4 1921.01   679.6 1923.49   706.6 1926.56   757.1 1938.83
   838.9 1953.12   867.2 1964.24     912 1988.14   932.7 1996.81  1035.5 2029.27
#Mann= 7 ,-1 , 0
       0      .1       0  219.29     .06       0   362.9      .1       0
  448.91    .045       0  557.05      .1       0  586.25     .06       0
  708.35      .1       0
Bank Sta=448.91,557.05
XS Rating Curve= 0 ,0
Exp/Cntr=0.3,0.1

Type RM Length L Ch R = 1 ,24622   ,252,245.3,240
XS GIS Cut Line= 3
2177978.60851935334636.602083641  2177499.713487335164.862541392
  2177329.378211335348.286389558
#Sta/Elev= 30
       0 2033.24    55.3 2007.06   126.5 1981.14   208.8 1943.57   229.7 1936.65
   246.1 1933.23   301.7 1929.11     318 1924.98   336.6 1916.06   355.1 1902.84
   363.1 1900.12   373.7  1893.5   382.6 1890.79   383.4 1890.61   411.9 1884.31
   441.1 1883.97   492.2 1885.96   509.6 1890.14   529.3 1899.56   538.6 1902.39
   564.9 1905.63   575.8 1904.55   582.9 1906.67   633.9 1912.29   656.2 1911.59
   736.1 1925.26   758.2 1933.16   838.2 1974.67   910.2 1997.79   963.3 2018.77
#Mann= 7 ,-1 , 0
       0      .1       0   18.33      .1       0  195.41     .06       0
   382.6    .045       0   383.4    .045       0   509.6     .06       0
   655.9      .1       0
Bank Sta=383.4,509.6
XS Rating Curve= 0 ,0
Exp/Cntr=0.3,0.1

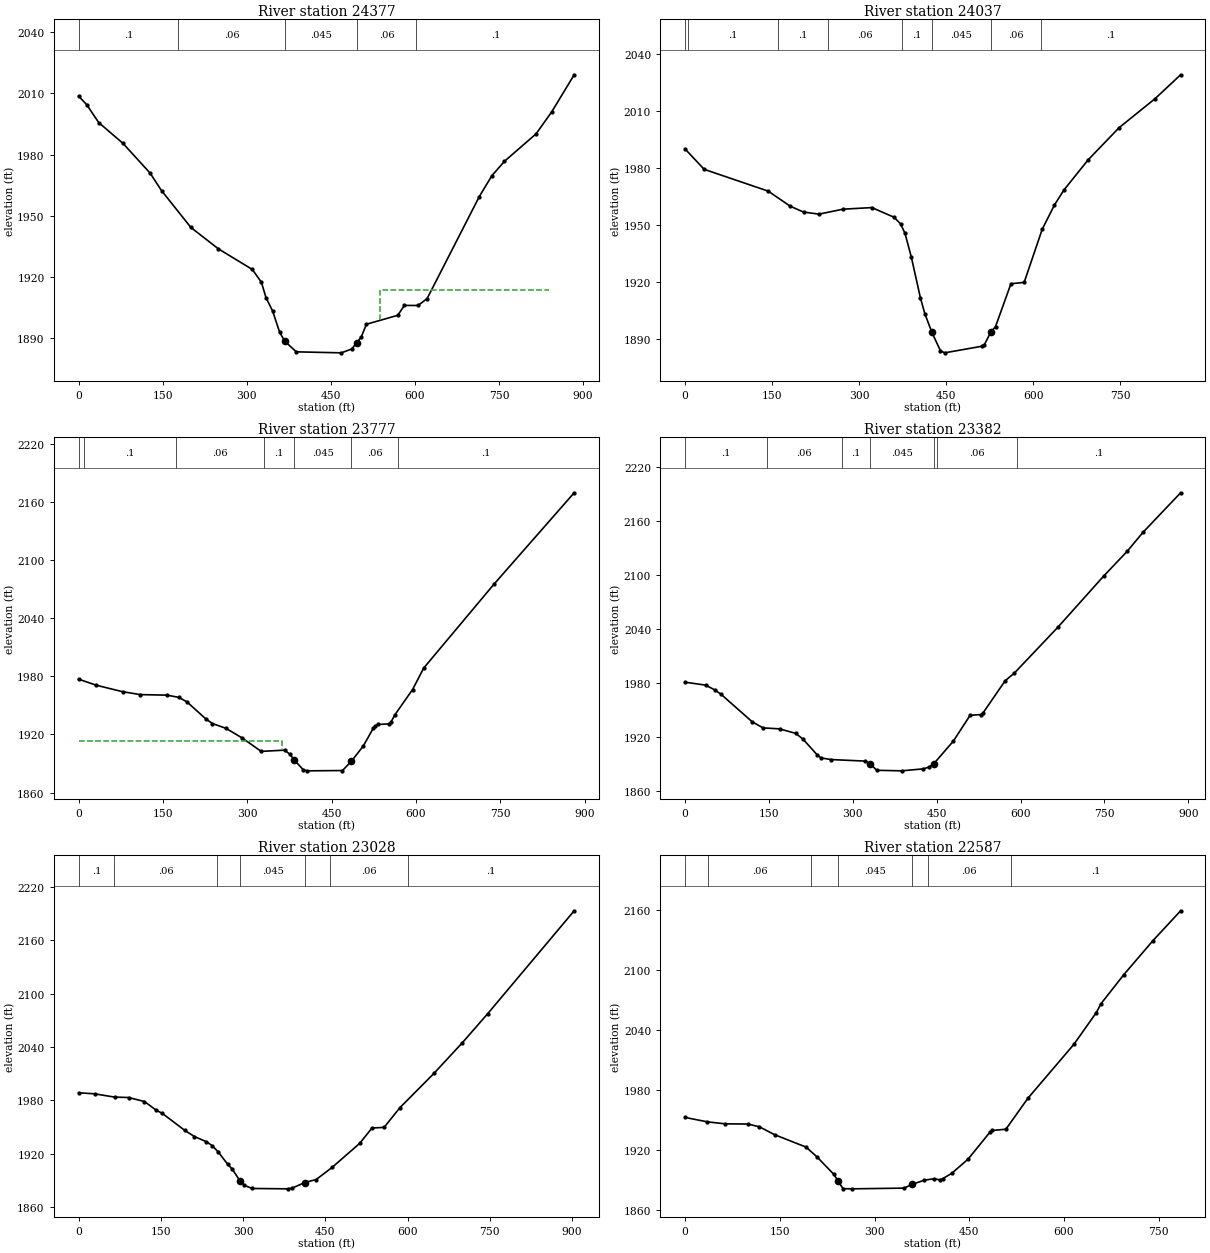
Type RM Length L Ch R = 1 ,24377   ,345.8,340.1,332.9
XS GIS Cut Line= 2
2177730.55619031334476.0043029092177212.34956402335192.217480789
#Sta/Elev= 30
       0 2008.67    14.3 2004.56    35.8 1995.73    79.1 1985.52   127.5 1970.93
   147.9 1962.33   200.3 1944.24   249.1 1933.81   309.9 1923.64   326.1 1917.35
   334.2 1909.86     346 1903.28   358.5 1892.91   367.8 1888.41   388.3 1883.23
   468.6 1882.74   486.9 1884.61   496.3 1887.67   504.3  1890.6   513.4 1896.77
   569.2 1901.15   581.2 1906.01   605.5 1905.97   621.7 1909.38   714.8 1959.44
   737.2 1969.65   759.6 1976.71   816.1 1990.21   844.1 2001.05     884 2019.17
#Mann= 5 ,-1 , 0
       0      .1       0  177.45     .06       0   367.8    .045       0
   496.3     .06       0  602.72      .1       0
#XS Ineff= 1 ,-1
  537.63   839.5 1913.37
Permanent Ineff=
       F
Bank Sta=367.8,496.3
XS Rating Curve= 0 ,0
Exp/Cntr=0.3,0.1

Type RM Length L Ch R = 1 ,24037   ,258.1,260.1,262.4
XS GIS Cut Line= 2
 2177413.3763833334265.5752979822176980.73715672335002.362538308
#Sta/Elev= 30
       0 1990.03    32.9 1979.31   143.3 1967.82   181.3 1959.87   204.2 1956.79
   230.8  1955.7   272.4 1958.31   322.1 1959.15   360.2 1954.06   371.6 1950.55
   379.2 1945.52     390 1933.14   405.8 1911.48   413.4  1903.2  425.57 1893.35
   440.1 1883.77   447.6 1882.59   512.3  1886.1   516.1 1886.93  527.061893.538
   535.2 1896.41   561.8 1919.01   584.6 1919.72   615.8 1947.77   636.9 1960.55
   653.1  1968.4     695 1984.34   748.2 2001.24   810.2 2016.53   854.4 2029.15
#Mann= 8 ,-1 , 0
       0     .12       0    4.25      .1       0  159.96      .1       0
  247.25     .06       0  373.22      .1       0  425.57    .045       0
  527.06     .06       0  613.86      .1       0
Bank Sta=425.57,527.06
XS Rating Curve= 0 ,0
Exp/Cntr=0.3,0.1

Type RM Length L Ch R = 1 ,23777   ,385.5,395.2,406.6
XS GIS Cut Line= 2
2177184.20984688334178.7696973092176705.73737864334919.029043555
#Sta/Elev= 30
       0 1976.98    31.4 1970.72    78.6 1963.98   109.9 1961.03   157.4 1960.48
   178.7 1958.11     193 1953.38   226.2 1935.95     238 1931.19   262.2 1926.21
   291.3 1916.13   324.7 1902.44   366.2 1903.72   375.7 1899.51  383.371893.737
   399.4 1883.54   406.5 1882.37   469.3 1882.68  484.951892.127   506.2 1907.87
   523.9  1926.2   527.5 1928.72   531.8  1930.2   551.3 1930.82   555.2 1932.34
   562.5  1940.2     594 1966.29   613.8 1988.44   738.5 2074.81   881.4 2169.32
#Mann= 7 ,-1 , 0
       0      .1       0   10.02      .1       0  172.83     .06       0
  330.45      .1       0  383.37    .045       0  484.95     .06       0
  568.61      .1       0
#XS Ineff= 2 , 0
          361.06 1913.32
Permanent Ineff=
       F       F
Bank Sta=383.37,484.95
XS Rating Curve= 0 ,0
Exp/Cntr=0.3,0.1

Type RM Length L Ch R = 1 ,23382   ,371.2,353.2,332.7
XS GIS Cut Line= 2
2176923.79304488334008.6309299772176302.26508847334640.575532228
#Sta/Elev= 30
       0 1980.72    36.6 1977.49    52.9 1972.21    64.3 1967.28   120.2 1936.58
   139.5  1929.9   168.9 1928.83   197.8  1923.8   210.7 1917.53   236.2 1899.96
   243.1 1896.51   261.2 1894.67     322 1892.97  330.341890.192   342.9 1882.74
   387.5 1882.13   426.4 1884.36   437.1 1886.48  444.821890.011   479.8 1915.19
   509.9 1943.93   529.1 1944.71   533.1 1946.63   572.6 1982.41   588.8 1990.76
   667.2 2042.13   748.9 2098.88   790.7 2126.26     819 2147.36   886.4 2191.41
#Mann= 7 ,-1 , 0
       0      .1       0  146.25     .06       0  280.34      .1       0
  330.34    .045       0  444.82      .1       0  451.35     .06       0
   593.4      .1       0
Bank Sta=330.34,444.82
XS Rating Curve= 0 ,0
Exp/Cntr=0.3,0.1

Type RM Length L Ch R = 1 ,23028   ,443.1,441,438.9
XS GIS Cut Line= 2
2176532.82072972333746.1124261472176141.15386213334560.695770726
#Sta/Elev= 30
       0  1988.6    29.1 1987.44    65.5 1983.75      91 1983.29   120.1 1978.78
   141.2 1969.16   152.9 1965.34   193.3 1946.45   211.1 1939.44   232.7 1933.69
   243.9 1929.04   254.8 1921.98     272 1908.12   280.3 1902.75  294.731889.192
   302.1 1884.58   316.7 1881.02   382.2 1880.61   389.5 1881.46  412.631887.732
   433.2 1891.04   462.3 1904.67   512.9 1931.87   535.1 1948.98   557.2 1949.71
   586.1  1971.9     648 2010.32   699.8 2044.78   746.3 2077.61   903.9 2193.22
#Mann= 7 ,-1 , 0
       0      .1       0   65.01     .06       0  251.75      .1       0
  294.73    .045       0  412.63      .1       0  458.62     .06       0
  601.23      .1       0
Bank Sta=294.73,412.63
XS Rating Curve= 0 ,0
Exp/Cntr=0.3,0.1

Type RM Length L Ch R = 1 ,22587   ,465.1,491.9,517.4
XS GIS Cut Line= 2
2176091.15396214333625.2793344712175776.57060181334344.029209316
#Sta/Elev= 30
       0 1952.18    35.2 1947.75    63.8 1945.76    99.3 1945.58   117.6 1942.82
   141.6 1934.92   191.5  1922.5   208.9 1912.66   235.7 1895.09  241.911888.769
   250.1  1880.9   263.7 1880.73   346.8 1881.45   359.61885.274     379 1889.39
   393.3 1890.78   404.1 1889.74   408.2    1891     422 1896.19     448 1910.41
     483 1937.67   486.4 1939.13   507.9 1940.38   542.7 1971.31   615.4 2025.15
   651.2 2057.15   658.3 2065.79   694.6    2095   740.7 2129.02   784.6 2158.93
#Mann= 7 ,-1 , 0
       0      .1       0   36.33     .06       0  198.99      .1       0
  241.91    .045       0   359.6      .1       0  384.06     .06       0
  515.51      .1       0
Bank Sta=241.91,359.6
XS Rating Curve= 0 ,0
Exp/Cntr=0.3,0.1

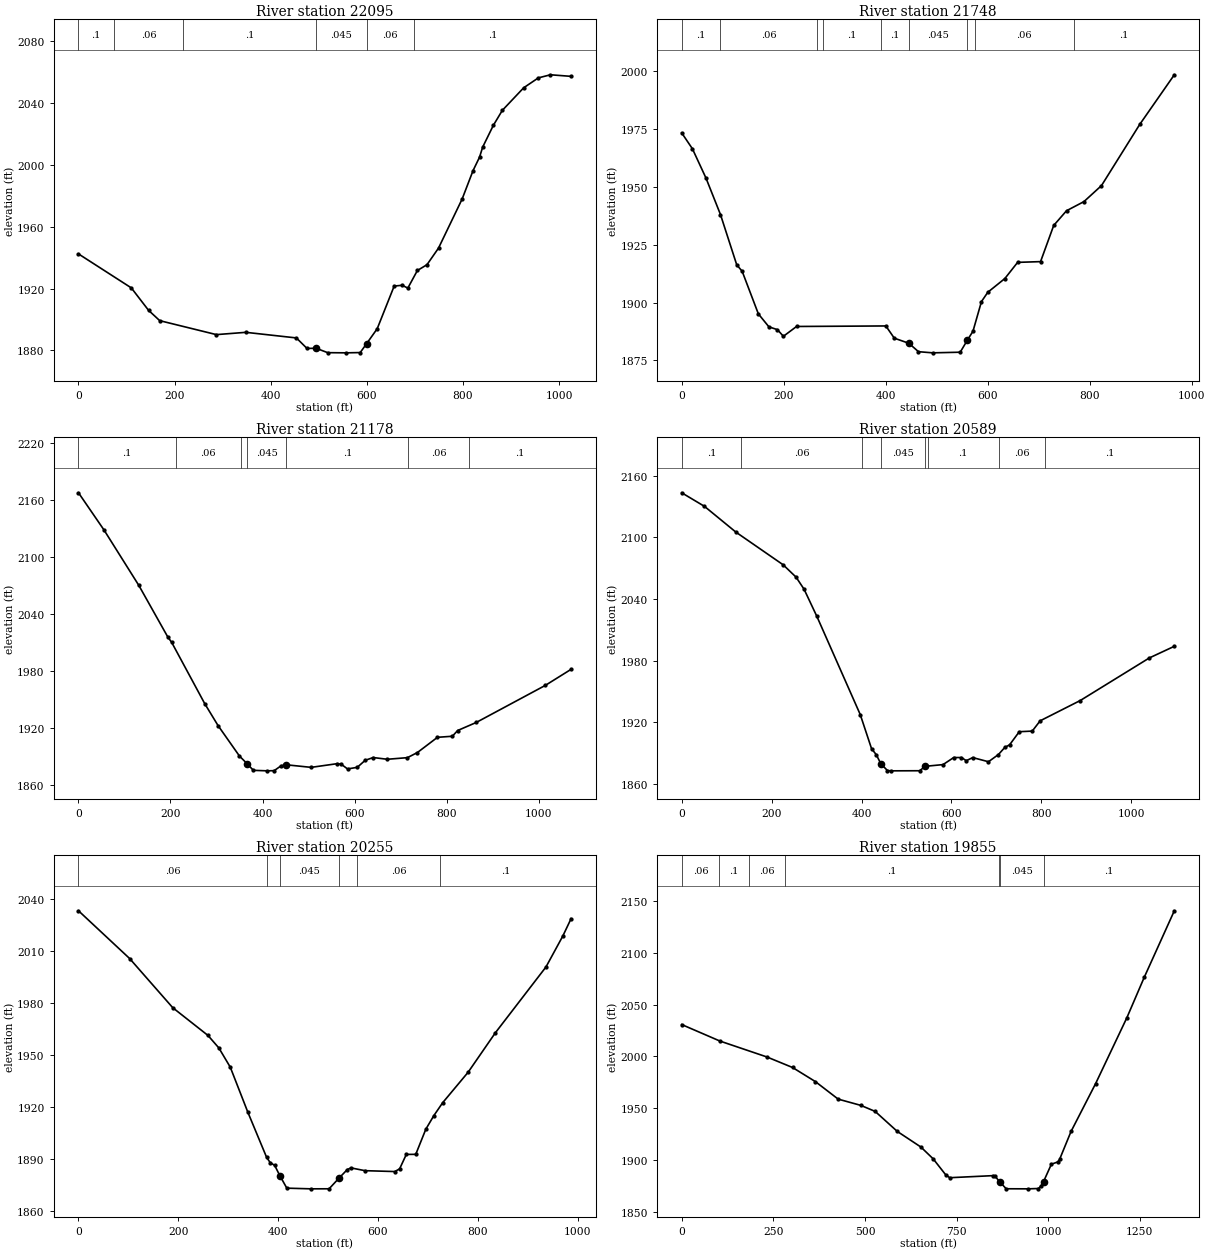
Type RM Length L Ch R = 1 ,22095   ,349.5,347.2,343.9
XS GIS Cut Line= 2
2175951.57057989333479.4459647242175109.90395613334064.862444803
#Sta/Elev= 30
       0 1942.44   109.9 1920.45   145.8 1905.93   169.1 1899.22     287 1890.18
   348.3 1891.66   453.5 1888.03   475.6 1881.23   494.61881.333   518.7 1878.49
   557.4 1878.38   586.3 1878.56  599.421884.216   621.7 1893.99     657 1921.61
   673.8 1922.14   685.4 1920.29   705.3  1931.7   725.3 1935.46   749.3 1946.21
   798.5 1978.02   821.2  1996.4   834.7 2005.11   841.2  2011.6   863.4  2025.7
   882.2 2035.44   926.6 2050.03   957.1 2056.44   982.3 2058.44  1025.2 2057.42
#Mann= 6 ,-1 , 0
       0      .1       0   74.02     .06       0  217.53      .1       0
   494.6    .045       0  599.42     .06       0  698.47      .1       0
Bank Sta=494.6,599.42
XS Rating Curve= 0 ,0
Exp/Cntr=0.3,0.1

Type RM Length L Ch R = 1 ,21748   ,574.5,570.4,561.1
XS GIS Cut Line= 2
2175674.48714456333216.9458335642174914.07068639333812.779287562
#Sta/Elev= 30
       0 1973.41      21 1966.53    47.5 1953.91      76 1938.08   107.9 1916.31
   118.5 1913.54   150.3 1895.08     171 1889.47   187.7 1888.25   199.4 1885.38
   225.2 1889.63   400.3 1889.86   416.9 1884.56  445.37 1882.37   464.3 1878.72
     492 1878.22   546.1 1878.49  559.981883.623   571.2  1887.6   587.8 1900.41
   600.3 1904.45   633.7 1910.38   658.7 1917.38   703.7  1917.7   729.5 1933.36
   754.6 1939.72   788.8 1943.68   823.2 1950.61   898.1 1977.06     966 1998.57
#Mann= 9 ,-1 , 0
       0      .1       0   75.36     .06       0  266.11      .1       0
  276.46      .1       0  389.88      .1       0  445.37    .045       0
  559.98      .1       0  574.61     .06       0  769.15      .1       0
Bank Sta=445.37,559.98
XS Rating Curve= 0 ,0
Exp/Cntr=0.3,0.1

Type RM Length L Ch R = 1 ,21178   ,600,588.5,573.6
XS GIS Cut Line= 3
2175243.23735088332746.1124576482174907.82069889333135.695996061
2174541.15378131333554.445814729
#Sta/Elev= 30
       0 2167.95    55.4 2128.76   131.1 2070.28   193.9 2016.01   202.6 2010.12
   274.5 1945.42   303.3 1922.41   349.8 1890.28  366.731882.016   380.1 1875.16
   410.4 1874.62   425.3 1874.81   440.7 1880.04  451.871880.991   505.7 1878.29
   562.3 1882.18     571 1881.63   584.8 1876.63   605.9 1878.31   623.3 1885.77
   640.6 1888.65   671.3 1886.82     715 1888.53   736.7 1893.94   780.3    1910
   812.6  1911.1   824.2 1917.17   864.5 1925.64  1014.9 1964.81  1070.7 1981.71
#Mann= 7 ,-1 , 0
       0      .1       0  211.71     .06       0  352.16      .1       0
  366.73    .045       0  451.87      .1       0  717.29     .06       0
  848.63      .1       0
Bank Sta=366.73,451.87
XS Rating Curve= 0 ,0
Exp/Cntr=0.3,0.1

Type RM Length L Ch R = 1 ,20589   ,323,334.4,345.5
XS GIS Cut Line= 2
2174641.15390939332354.4459181432174207.82045847 333360.69587414
#Sta/Elev= 30
       0 2143.41    50.6 2130.19   120.5 2105.11   225.7 2073.27   254.3  2061.3
   272.1 2049.55   300.7 2022.98   397.1 1927.48   422.1 1894.45   432.9 1888.29
  442.831879.655   457.5 1873.04   464.9 1872.72   529.3 1872.82  541.231877.112
   581.2 1878.79   604.9 1885.66   622.2 1885.68   632.9  1882.6   647.3 1885.62
   682.3 1881.58   704.3 1888.55   718.6 1895.52   729.3 1898.07   750.8 1910.82
   779.6  1911.4   797.2 1921.41   886.5 1941.19  1040.1 1982.64  1095.6 1993.96
#Mann= 8 ,-1 , 0
       0      .1       0   132.5     .06       0  401.71      .1       0
  442.83    .045       0  541.23      .1       0  547.84      .1       0
  704.68     .06       0  807.56      .1       0
Bank Sta=442.83,541.23
XS Rating Curve= 0 ,0
Exp/Cntr=0.3,0.1

Type RM Length L Ch R = 1 ,20255   ,378,400.2,421.2
XS GIS Cut Line= 2
2174430.73733547332258.6124483942173855.73717314333060.695817977
#Sta/Elev= 30
       0 2033.24   102.5 2005.66   188.9 1977.26   259.4 1961.26   281.2 1954.05
   304.1 1942.94   339.3 1916.93   376.9 1890.87     384 1887.86   393.1  1886.2
  403.281880.356   417.4 1873.07   465.8 1872.68   502.1 1872.71  521.321878.671
   538.5  1883.8   545.9 1884.78     574 1883.17   633.8 1882.66   643.4 1884.24
   656.8 1892.56   675.7  1892.6   695.9 1907.13     712 1914.98   729.6  1922.4
   780.7 1940.04   835.4 1962.87   936.6  2000.8   970.4 2018.69   986.9  2028.7
#Mann= 6 ,-1 , 0
       0     .06       0  378.05      .1       0  403.28    .045       0
  521.32      .1       0  557.92     .06       0  723.97      .1       0
Bank Sta=403.28,521.32
XS Rating Curve= 0 ,0
Exp/Cntr=0.3,0.1

Type RM Length L Ch R = 1 ,19855   ,497.2,504.5,509.1
XS GIS Cut Line= 3
2174658.88322388331979.9563359812173920.32070538332348.195930645
2173486.98725447332633.612682641
#Sta/Elev= 30
       0 2030.88   104.4 2014.91   232.7 1999.52   302.4 1989.37   364.7 1975.75
     427 1958.78   488.8 1952.74   527.9  1946.9   588.3 1927.56   652.7 1912.47
   686.2 1901.05   720.3 1885.67   731.3 1882.82   850.3 1884.83   855.6 1884.18
     866 1879.44   867.5 1878.99   885.4 1872.13   944.7 1872.06   973.2 1872.37
   979.9 1874.53   987.4 1879.08  1008.7 1895.86    1027 1898.18    1031 1900.44
  1062.4 1927.54  1129.5 1973.83  1214.8 2037.53  1262.1 2076.53  1344.2 2140.87
#Mann= 7 ,-1 , 0
       0     .06       0  102.84      .1       0  182.48     .06       0
  280.81      .1       0     866      .1       0   867.5    .045       0
   987.4      .1       0
Bank Sta=867.5,987.4
XS Rating Curve= 0 ,0
Exp/Cntr=0.3,0.1

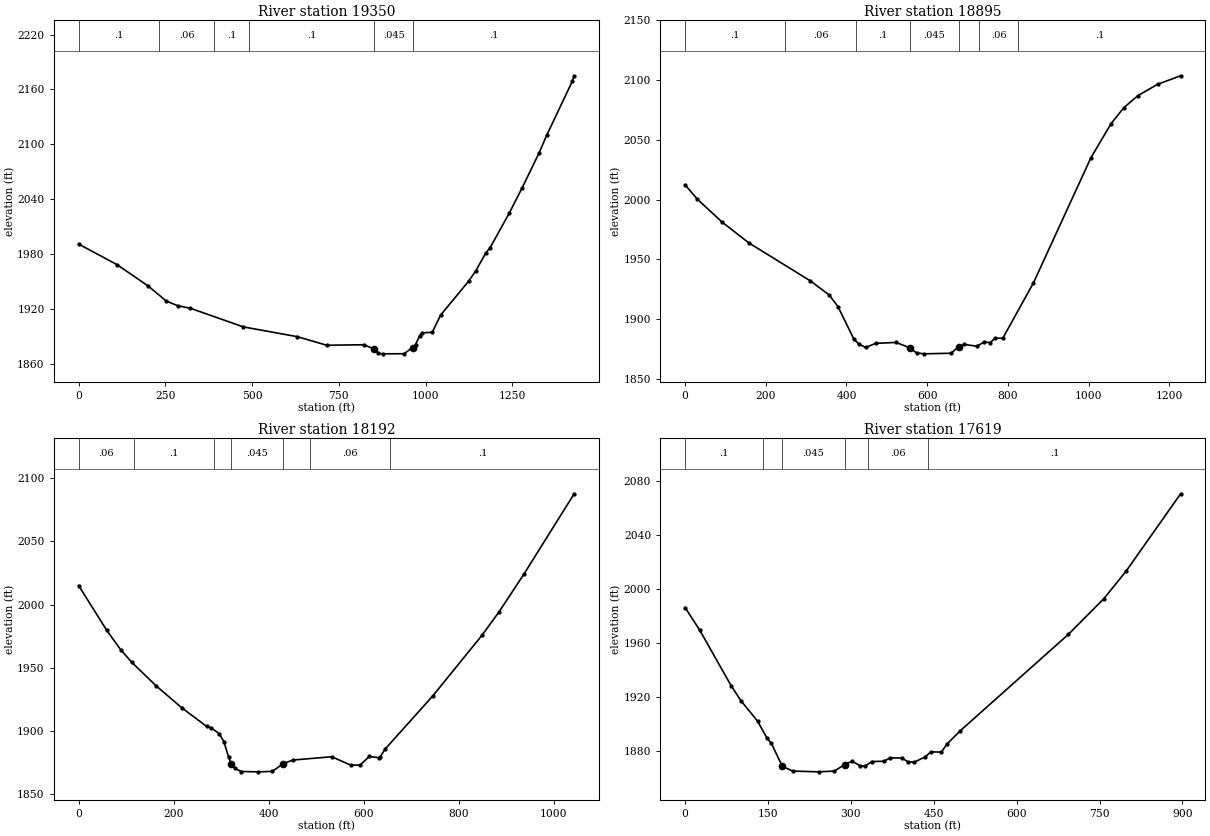
Type RM Length L Ch R = 1 ,19350   ,459.8,455.1,450.5
XS GIS Cut Line= 2
2174401.52257605  331539.98389882173136.98729831332204.445890054
#Sta/Elev= 30
       0 1991.08   111.3 1968.46   200.3  1945.3   252.1 1928.98   285.4 1923.71
   321.8 1920.95   474.5 1900.61   630.7 1889.85   715.4  1880.5   822.3 1881.06
   852.5 1876.27   863.6 1871.57   878.5 1871.12   937.8 1871.24   963.2 1878.04
   971.1 1881.18   983.4 1891.03   989.7 1894.07  1019.3 1894.65  1043.4 1913.38
  1124.5 1950.66    1145 1961.85  1173.8 1981.45  1186.1 1987.08  1241.7 2025.12
  1278.8 2052.71  1326.9  2090.3  1349.5  2110.1  1423.3 2169.14  1428.5 2174.99
#Mann= 6 ,-1 , 0
       0      .1       0  232.38     .06       0  388.96      .1       0
  492.46      .1       0   852.5    .045       0   963.2      .1       0
Bank Sta=852.5,963.2
XS Rating Curve= 0 ,0
Exp/Cntr=0.3,0.1

Type RM Length L Ch R = 1 ,18895   ,752.7,703.7,647
XS GIS Cut Line= 2
2173874.48713563  331246.1125049 2172839.0705713331906.529163063
#Sta/Elev= 30
       0 2012.43    30.5 2000.37      91 1981.45   157.7 1963.89   309.8  1932.2
   357.3 1920.23     379 1910.48   417.9 1883.56     431 1879.07   447.6 1876.36
   472.4 1879.83     523 1880.57  556.741876.058   573.5 1871.84   591.8 1871.03
   659.1 1871.54  677.911876.957   692.3 1878.87   723.2 1877.42   740.9 1880.89
   756.5  1880.5   768.1 1884.09   787.4 1884.13   863.4 1930.45  1005.9 2035.21
  1055.8 2063.67  1087.2 2076.93  1122.2 2087.05  1171.4 2096.61  1228.1 2103.66
#Mann= 7 ,-1 , 0
       0      .1       0  248.06     .06       0   424.7      .1       0
  556.74    .045       0  677.91    .025       0  727.63     .06       0
  825.21      .1       0
Bank Sta=556.74,677.91
XS Rating Curve= 0 ,0
Exp/Cntr=0.3,0.1

Type RM Length L Ch R = 1 ,18192   ,598.7,572.6,544.8
XS GIS Cut Line= 2
2172828.65392546330846.1126487262172741.15410048331885.695871398
#Sta/Elev= 30
       0 2015.17      59 1979.83    88.6  1964.4   111.7 1954.48   162.8 1935.96
     217  1918.5   269.7 1903.66   279.6  1902.5   296.2 1897.89   305.9  1891.6
   315.8 1879.34  321.511873.992   329.6 1870.47   342.1 1868.03   378.5 1867.78
     408 1868.15  429.771874.073   451.1 1877.12   533.1 1879.72   572.6 1873.12
   592.4 1873.11   612.1 1879.97   631.9 1878.92   635.2 1879.81     645 1885.66
   745.7 1927.89   849.2 1975.79   885.4 1994.48   938.1 2024.53  1043.3 2087.75
#Mann= 7 ,-1 , 0
       0     .06       0  116.11      .1       0  285.67    .025       0
  321.51    .045       0  429.77      .1       0  486.38     .06       0
   656.5      .1       0
Bank Sta=321.51,429.77
XS Rating Curve= 0 ,0
Exp/Cntr=0.3,0.1

Type RM Length L Ch R = 1 ,17619   ,459.9,447.4,433.7
XS GIS Cut Line= 2
2172152.44689395 331097.501253562172515.53482154331917.474656326
#Sta/Elev= 30
       0 1986.44    26.2  1969.9    83.6 1928.35   101.5 1917.23   131.3 1902.19
   148.2 1889.73   156.1 1885.79     176 1868.79   194.8 1865.29   241.5 1864.72
   270.2 1865.28   288.5 1870.08   302.5 1872.58   316.8 1869.25   325.2 1868.91
   338.3 1872.37   359.9 1872.55   370.6 1875.02   392.2 1875.04   402.9 1872.24
   414.8 1871.89   434.7 1875.83   444.6 1879.49   463.9 1879.35   473.9 1885.31
   498.2 1895.24   693.6 1966.59     758 1993.09   798.1 2013.46   896.8 2070.79
#Mann= 6 ,-1 , 0
       0      .1       0  140.32      .1       0     176    .045       0
   288.5      .1       0  331.86     .06       0  440.04      .1       0
Bank Sta=176,288.5
XS Rating Curve= 0 ,0
Exp/Cntr=0.3,0.1