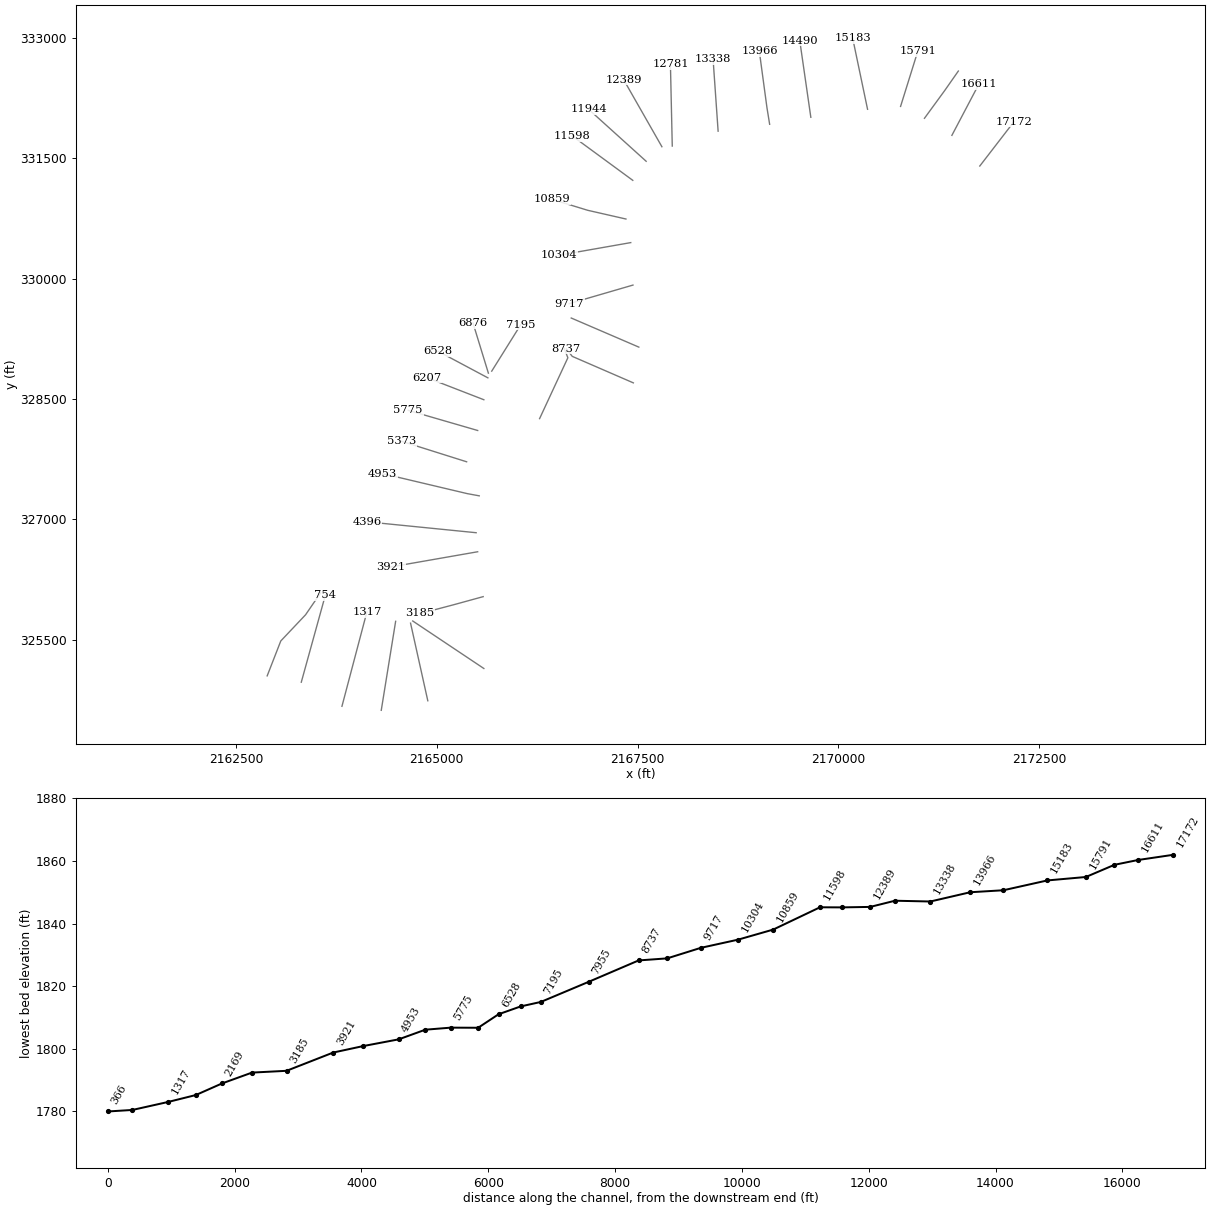
HEC-RAS study ANTHONYCK.prj: ANTHONYCK

--- ANTHONYCK.g01 (geometry) --- (continued)

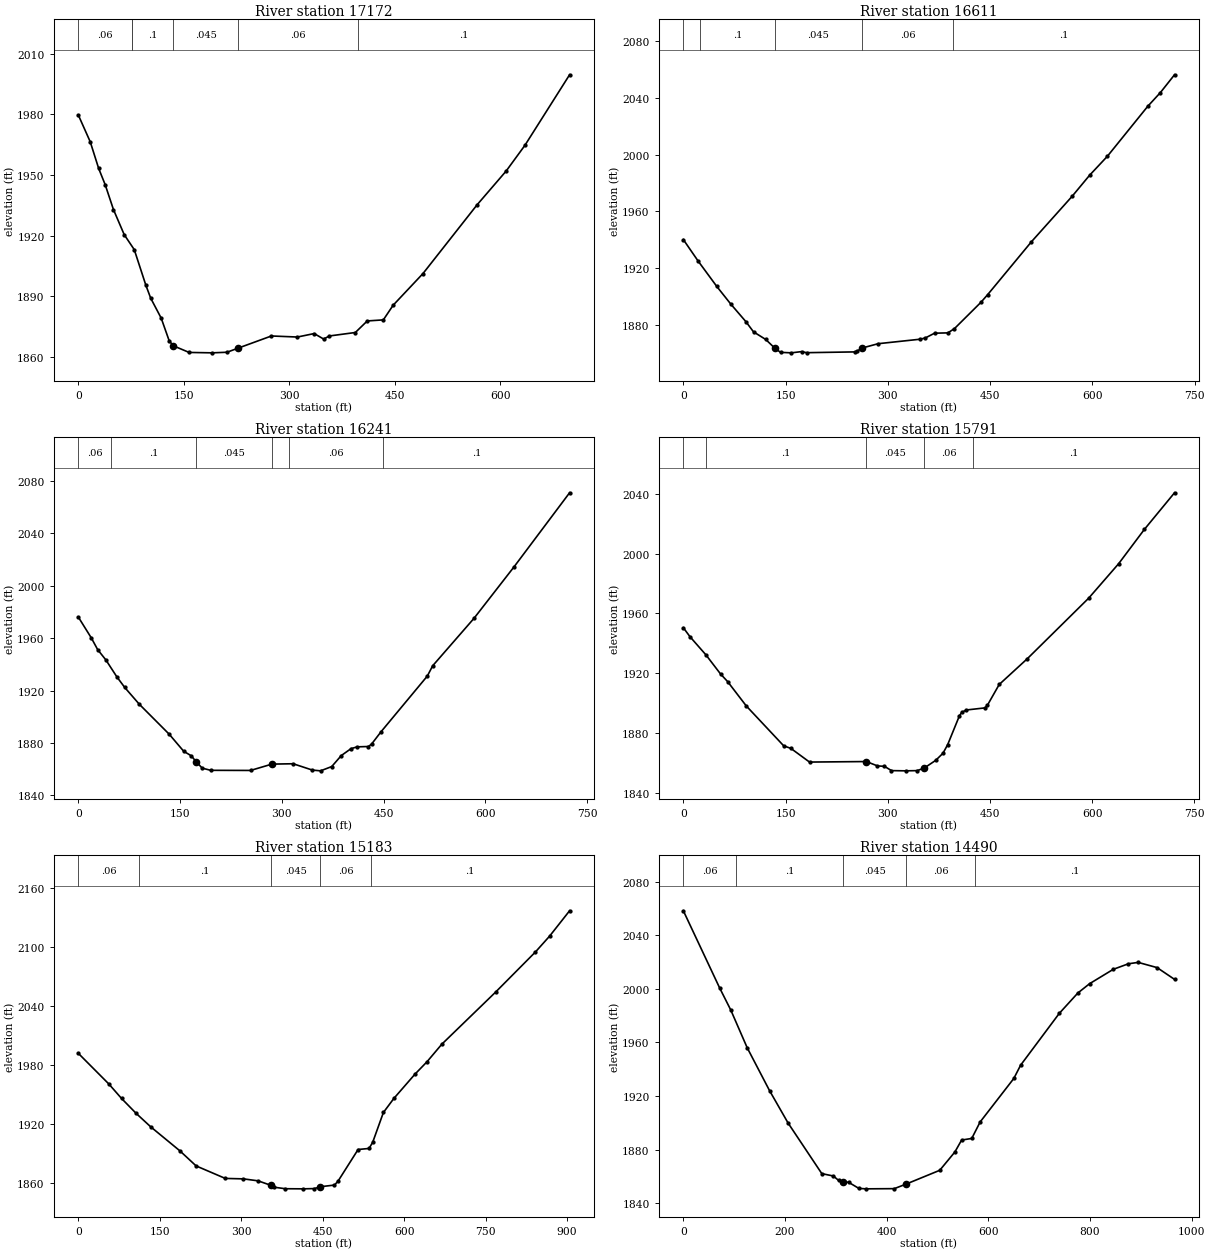
Type RM Length L Ch R = 1 ,17172   ,541.3,560.7,565.5
XS GIS Cut Line= 2
2171759.96384421331402.9825220532172186.09649681331956.242929811
#Sta/Elev= 30
       0 1979.51    16.8 1966.39    28.8  1953.2    38.1 1945.13    49.8 1932.88
    65.1 1920.46    79.4 1913.04      96 1895.32   102.8 1889.01   117.7 1879.15
   129.1  1867.9     135 1865.47   157.4 1862.19   190.2 1861.99   211.2 1862.28
   226.4 1864.23   274.4 1870.33   311.3 1869.81   335.2 1871.52   348.6 1868.82
   356.9 1870.34   393.7 1872.05   410.7 1877.77   433.5 1878.29   447.5 1885.56
   489.9 1901.22   566.8 1935.21   608.2 1951.95   634.7 1964.58   698.3 1999.53
#Mann= 6 ,-1 , 0
       0     .06       0    75.8      .1       0    76.4      .1       0
     135    .045       0   226.4     .06       0  398.06      .1       0
Bank Sta=135,226.4
XS Rating Curve= 0 ,0
Exp/Cntr=0.3,0.1

Type RM Length L Ch R = 1 ,16611   ,382,369.7,363.5
XS GIS Cut Line= 2
2171412.68169181 331785.00151898 2171748.0983438332422.501556307
#Sta/Elev= 30
       0 1940.19    21.7 1925.04    49.1 1907.11    69.7 1894.63    91.7 1882.33
   102.9 1875.12   120.8 1869.75  134.251863.564   142.6 1860.65   158.5 1860.31
   173.3 1861.18   180.7 1860.42   251.1 1860.97   254.4  1861.3  261.951863.687
   285.9 1866.77   347.5 1869.93   354.9 1870.81   368.5 1874.17     388 1874.39
   397.7 1877.43   436.4 1895.91   446.3 1901.33   510.6 1938.69     570 1970.59
   595.9 1985.59   621.9 1998.93   681.2 2034.22   699.7 2043.89   720.4 2056.43
#Mann= 5 ,-1 , 0
       0     .06       0   24.46      .1       0  134.25    .045       0
  261.95     .06       0  395.56      .1       0
Bank Sta=134.25,261.95
XS Rating Curve= 0 ,0
Exp/Cntr=0.3,0.1

Type RM Length L Ch R = 1 ,16241   ,432.3,450.5,459.8
XS GIS Cut Line= 3
 2171071.0150523331997.5014220632171324.64172339332345.280939037
2171492.84428765332586.088801056
#Sta/Elev= 30
       0 1976.02      19 1960.24    28.4 1951.27    40.5 1943.42    56.7 1930.48
    68.3 1922.41    89.7 1909.65   133.9 1886.71   155.2 1873.74   166.4 1870.25
   173.81865.627   182.6 1860.82   195.1 1859.18   253.8 1859.08  285.291863.912
   316.6 1864.19     345 1859.35     357 1858.78   373.5 1862.04   387.6 1870.44
   401.9  1875.7   411.1 1877.09   427.6 1877.35   432.3 1879.23   446.3 1888.66
   514.4 1931.08   522.4 1938.99   583.1 1975.06     642 2014.25   724.2 2070.98
#Mann= 6 ,-1 , 0
       0     .06       0   47.85      .1       0   173.8    .045       0
  285.29    .025       0  310.02     .06       0  449.22      .1       0
Bank Sta=173.8,285.29
XS Rating Curve= 0 ,0
Exp/Cntr=0.3,0.1

Type RM Length L Ch R = 1 ,15791   ,579,607.5,624.4
XS GIS Cut Line= 2
2170773.68785128 332145.418120982170988.26955398332833.688363035
#Sta/Elev= 30
       0 1950.47     9.9  1944.4    33.1 1932.38    54.6 1919.59    64.9 1914.55
    92.4 1898.22   147.4 1871.54   157.7 1869.92   185.2 1860.74  268.641861.086
   284.9 1858.18   295.2 1857.88   305.5 1855.03   326.1 1854.88   343.3 1855.02
  353.821856.831   370.3 1861.85   381.1 1866.64     388 1872.42   405.1 1891.53
   408.6 1893.94   415.4 1895.53   442.9 1896.94   446.4 1898.79   463.6 1912.57
   504.8 1929.76     595 1970.27   638.8  1993.2   676.6 2016.13   720.9 2040.63
#Mann= 5 ,-1 , 0
       0     .06       0   32.59      .1       0  268.64    .045       0
  353.82     .06       0  425.84      .1       0
Bank Sta=268.64,353.82
XS Rating Curve= 0 ,0
Exp/Cntr=0.3,0.1

Type RM Length L Ch R = 1 ,15183   ,695.1,693.1,689.8
XS GIS Cut Line= 2
 2170362.6818233332110.0015251492170177.26519939332995.418061391
#Sta/Elev= 30
       0 1991.82    55.9 1960.75    79.4 1945.94   106.2 1930.78     133 1917.07
   186.7  1892.6   216.8 1877.14   270.5  1864.4     304 1863.94   330.8 1861.94
  353.98 1857.48     361  1855.4   381.1 1853.89   414.2 1853.78   434.7 1854.04
  445.761855.951   471.6 1857.62   478.3 1861.74   515.1 1893.88   535.3 1894.95
     542 1901.25   561.7 1931.62   581.1 1946.02   619.9 1970.71   642.1 1983.38
   669.3 2001.22   768.2 2054.24   841.7 2095.24   867.9 2111.45   904.6 2137.23
#Mann= 5 ,-1 , 0
       0     .06       0  112.21      .1       0  353.98    .045       0
  445.76     .06       0  537.96      .1       0
Bank Sta=353.98,445.76
XS Rating Curve= 0 ,0
Exp/Cntr=0.3,0.1

Type RM Length L Ch R = 1 ,14490   ,524.8,524.2,522.8
XS GIS Cut Line= 2
2169656.43159539332010.0013970582169518.47817451332966.432559875
#Sta/Elev= 30
       0 2058.41    71.4 2000.76    93.4 1984.18   125.6 1956.07   169.6 1924.01
   206.1 1899.79   272.4 1862.01   295.2 1860.22   305.5  1856.9  314.151856.026
   325.4 1855.47   345.3 1850.97   358.9 1850.64   414.9 1850.78   438.51854.227
   504.4 1864.49   534.2 1878.18   547.5  1887.1   567.4 1888.29   583.9 1900.62
   650.2 1933.14   663.5 1943.02   739.7  1981.8   776.2 1996.99   799.2 2003.92
   845.8 2014.66   875.6 2018.81   894.8 2019.84     932 2015.95   966.3 2007.16
#Mann= 5 ,-1 , 0
       0     .06       0  103.44      .1       0  314.15    .045       0
   438.5     .06       0  573.27      .1       0
Bank Sta=314.15,438.5
XS Rating Curve= 0 ,0
Exp/Cntr=0.3,0.1

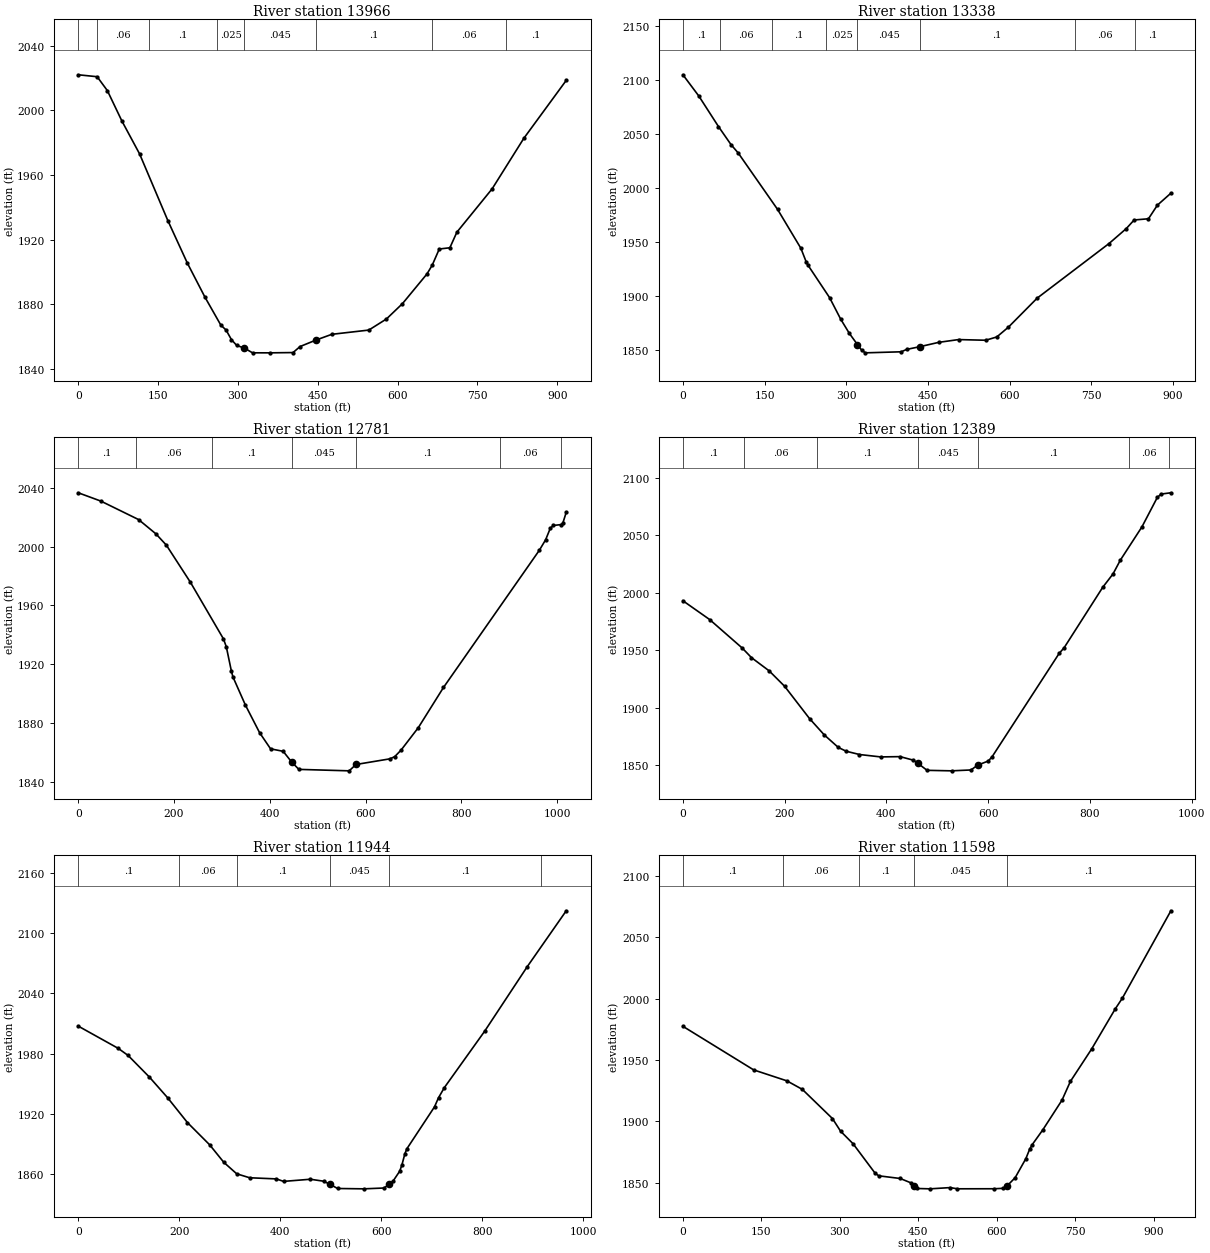
Type RM Length L Ch R = 1 ,13966   ,631.9,627.9,622.5
XS GIS Cut Line= 3
2169143.61469921331922.9992877322169110.09972498332130.880093515
2169015.44252075332830.969630448
#Sta/Elev= 30
       0 2021.99    35.5 2020.79    54.7  2012.2      82  1993.4   115.3 1973.02
   168.4 1931.77     205 1905.51   238.1 1884.43   267.9 1867.16   277.8 1864.09
   287.9 1858.14   297.7  1854.6  312.351852.889   327.5 1850.01   360.6    1850
   403.6 1850.17   416.9 1853.91  446.391857.862   476.5 1861.46     546 1864.08
   579.1 1870.94   609.2 1880.42   655.3  1898.8   665.2 1904.26   678.4 1914.22
   698.3 1914.99   711.5 1924.64   777.8 1951.48   837.3  1982.7     917 2018.53
#Mann= 8 ,-1 , 0
       0      .1       0    35.6     .06       0  132.07      .1       0
  260.71    .025       0  312.35    .045       0  446.39      .1       0
   665.4     .06       0  803.39      .1       0
Bank Sta=312.35,446.39
XS Rating Curve= 0 ,0
Exp/Cntr=0.3,0.1

Type RM Length L Ch R = 1 ,13338   ,561.7,557.3,554.9
XS GIS Cut Line= 2
2168502.26494047331837.0847481492168439.76506548 332730.83460106
#Sta/Elev= 30
       0 2104.51    29.2 2084.85    65.3 2056.57    88.4 2039.79   101.5 2032.11
   173.9 1979.78   216.6 1943.83   226.5 1931.07   229.9 1927.99   269.3 1898.14
   289.7  1878.2   305.4 1865.18  320.441854.681   328.3 1849.42     335 1847.04
   400.8 1848.01   410.7 1850.21  434.891852.727   469.9 1856.78   506.1 1859.32
   555.8  1858.7   576.2 1861.73   597.4 1870.73   650.4  1897.7   782.3 1948.25
     814  1962.1   828.4 1970.06   854.7 1971.18   871.1 1983.78   895.9 1994.87
#Mann= 8 ,-1 , 0
       0      .1       0   68.42     .06       0  163.41      .1       0
  263.43    .025       0  320.44    .045       0  434.89      .1       0
  719.04     .06       0  829.15      .1       0
Bank Sta=320.44,434.89
XS Rating Curve= 0 ,0
Exp/Cntr=0.3,0.1

Type RM Length L Ch R = 1 ,12781   ,354.6,391.4,415.5
XS GIS Cut Line= 2
2167931.43176456331651.6681242292167908.51514372332670.418055221
#Sta/Elev= 30
       0 2036.83    47.2 2031.16     126 2018.56   162.1 2008.85     184 2001.13
   234.3 1975.78   303.2 1937.23   309.2  1931.8   319.6 1915.52   322.9 1911.39
   349.1 1892.07   378.7 1873.28   401.6 1862.29   427.9  1860.6  445.611853.305
   460.7 1848.28   565.7 1847.29  579.951851.619     651 1855.48   660.9    1857
     674 1861.39   710.1 1876.73   762.6  1904.1   962.8 1997.64   975.9 2004.77
   985.8 2012.72   992.3 2014.54  1008.8 2015.18    1012 2016.27    1019 2023.54
#Mann= 7 ,-1 , 0
       0      .1       0  121.15     .06       0  279.64      .1       0
  445.61    .045       0  579.95      .1       0  880.28     .06       0
 1007.67      .1       0
Bank Sta=445.61,579.95
XS Rating Curve= 0 ,0
Exp/Cntr=0.3,0.1

Type RM Length L Ch R = 1 ,12389   ,426.1,445.7,463.1
XS GIS Cut Line= 2
2167802.26502813 331643.334807562167327.26499389332476.668114647
#Sta/Elev= 30
       0 1993.02    52.6 1976.69   116.7 1951.92   134.8 1943.62   169.6 1932.12
   199.9 1918.76   248.9 1890.69   277.8 1876.54   305.6 1865.58   321.1 1862.32
   347.1 1859.49   388.7  1857.4   426.9 1857.65   452.9 1854.59   461.61851.956
   479.9 1845.75     528 1845.31   566.2 1846.07  579.451850.276   600.2 1853.82
   607.7  1857.5   739.6 1947.33   749.3 1952.19   825.3 2004.78   845.5 2016.38
   859.9 2028.34   902.3 2057.21   932.5 2082.78     940 2085.69   959.2  2086.8
#Mann= 7 ,-1 , 0
       0      .1       0  120.17     .06       0  264.05      .1       0
   461.6    .045       0  579.45      .1       0  876.76     .06       0
  954.78      .1       0
Bank Sta=461.6,579.45
XS Rating Curve= 0 ,0
Exp/Cntr=0.3,0.1

Type RM Length L Ch R = 1 ,11944   ,346.5,346,352.7
XS GIS Cut Line= 2
2167606.43175839331462.0848419822166889.76521271332110.001525149
#Sta/Elev= 30
       0 2007.32    79.1 1985.16    98.7 1978.08     141 1956.45   176.7 1936.07
   216.1 1911.23   260.1 1889.06   288.2 1871.56   313.7 1860.14   339.3  1856.2
   392.2 1855.06   406.4 1852.58   459.5 1854.72   485.6 1852.78   497.81849.794
   513.5  1845.5   565.6 1845.16   605.4 1845.99   615.7 1849.84   623.1 1852.79
   636.4 1862.74   640.8 1869.06   646.6 1880.05   650.5 1885.03   705.3 1926.88
   713.2 1935.93   724.8 1946.05   804.4 2002.12   888.5 2066.27   966.1 2122.26
#Mann= 6 ,-1 , 0
       0      .1       0  198.48     .06       0  313.63      .1       0
   497.8    .045       0   615.7      .1       0  917.05     .06       0
Bank Sta=497.8,615.7
XS Rating Curve= 0 ,0
Exp/Cntr=0.3,0.1

Type RM Length L Ch R = 1 ,11598   ,688.8,739,746.5
XS GIS Cut Line= 2
2167439.76509698331224.5846608132166687.68162739331776.668202311
#Sta/Elev= 30
       0 1977.46   135.3 1941.99   198.7  1933.1   228.3 1926.15   285.9 1902.39
   301.5 1892.09   325.4 1881.86   367.6 1857.84   374.6 1855.78   415.5 1853.61
   435.6 1850.12  441.931847.739     448 1845.48   472.5 1845.19   510.8  1846.2
   524.9 1845.22   595.3 1845.26   611.7 1845.61   618.7 1847.12   635.2 1854.25
   655.6 1869.69   662.9 1877.38   667.8 1881.13   688.2 1893.27   724.8 1917.37
   740.8 1932.59   781.8 1959.25   826.5 1991.58   840.3 2000.45     933  2071.5
#Mann= 5 ,-1 , 0
       0      .1       0  191.47     .06       0  335.77      .1       0
  441.93    .045       0   618.7      .1       0
Bank Sta=441.93,618.7
XS Rating Curve= 0 ,0
Exp/Cntr=0.3,0.1

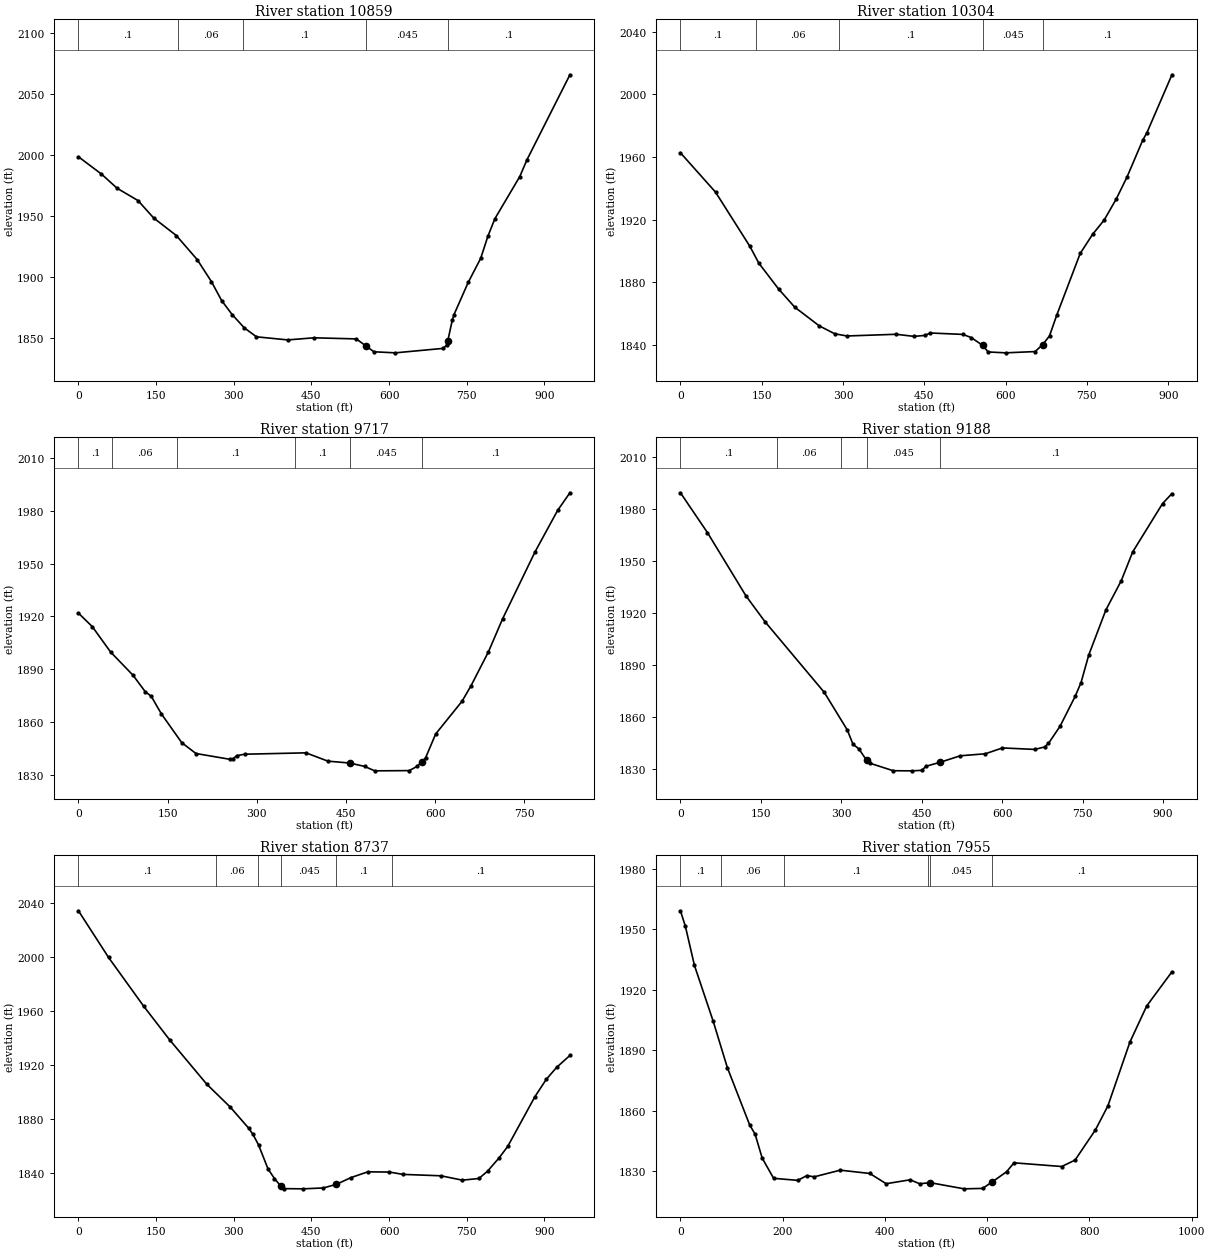
Type RM Length L Ch R = 1 ,10859   ,530.3,554.1,603.6
XS GIS Cut Line= 3
2167354.81119864330742.7965824012166879.81149247330851.130027145
2166438.14472489330986.546422973
#Sta/Elev= 30
       0  1998.4    44.4 1984.29    74.7 1972.66   115.1 1962.59   145.3 1948.35
   189.1 1933.98   229.5 1914.25   256.9 1896.27   276.6  1880.8   296.8 1869.39
   320.3  1858.5   343.9 1851.15   404.4 1848.62   454.9 1850.35   536.6 1849.44
     5561843.472   570.7 1838.91   612.1 1838.05   704.7 1841.71   711.7  1844.7
  713.261847.682     722 1864.76   725.4 1869.39   752.8 1895.69   776.9 1915.35
   790.6 1933.21   804.3 1947.77   852.4 1982.25   866.1 1995.83   949.2 2065.47
#Mann= 5 ,-1 , 0
       0      .1       0  192.66     .06       0   318.6      .1       0
     556    .045       0  713.26      .1       0
Bank Sta=556,713.26
XS Rating Curve= 0 ,0
Exp/Cntr=0.3,0.1

Type RM Length L Ch R = 1 ,10304   ,580.7,587.4,593.2
XS GIS Cut Line= 2
 2167414.6847521330448.8648061782166521.52316826330291.890964044
#Sta/Elev= 30
       0 1962.66    64.8  1937.5     128 1902.95   144.7 1892.11   181.3 1875.53
   210.9 1864.02   256.2 1852.05   284.6 1847.03   307.2  1845.6     398 1846.69
   431.2 1845.34   451.2 1845.97   461.2 1847.51   521.1 1846.61   536.7 1844.58
   557.8 1839.55   567.8 1835.39   599.9 1834.83   654.4 1835.64   668.6 1840.14
     681 1845.67   694.3 1858.85   737.6 1898.31   760.5 1910.54   781.8 1919.65
   804.3 1933.21   824.3 1947.37   852.9 1970.61   860.9 1975.61   906.9  2012.5
#Mann= 5 ,-1 , 0
       0      .1       0  139.55     .06       0  292.37      .1       0
   557.8    .045       0   668.6      .1       0
Bank Sta=557.8,668.6
XS Rating Curve= 0 ,0
Exp/Cntr=0.3,0.1

Type RM Length L Ch R = 1 ,9717    ,571.4,529.2,473.2
XS GIS Cut Line= 2
2167442.31135172329919.879921138 2166648.5612988329688.629727483
#Sta/Elev= 30
       0 1921.85    23.4 1914.14    54.2  1899.7    91.8 1886.55   112.3 1877.24
   122.5 1874.57   139.6 1864.55   173.8 1848.22   197.7 1842.06   255.8 1838.71
   259.2 1838.77   266.1 1840.83   279.7 1841.66   382.7 1842.44   419.8 1837.71
  456.021836.661   481.4 1834.73   498.4 1832.21   556.5 1832.34   570.2 1834.84
  577.411837.315   583.9 1839.54     601 1853.18   645.4 1871.79   660.6 1880.66
   689.7 1899.84   713.7 1918.71   768.4 1956.84   806.1  1980.2   826.8 1990.23
#Mann= 6 ,-1 , 0
       0      .1       0   56.84     .06       0  166.46      .1       0
  364.63      .1       0  456.02    .045       0  577.41      .1       0
Bank Sta=456.02,577.41
XS Rating Curve= 0 ,0
Exp/Cntr=0.3,0.1

Type RM Length L Ch R = 1 ,9188    ,445.7,450.5,447.4
XS GIS Cut Line= 2
2167515.22787255329146.9631598892166673.56124881329509.463091061
#Sta/Elev= 30
       0  1989.2    50.3 1966.27   122.1 1929.78   157.5 1914.92   268.2  1874.1
   311.1 1852.42   321.8 1844.16   332.5 1841.59  346.931835.027     353 1833.27
   396.8 1828.91   432.5 1828.85   450.4 1829.15   457.5 1831.44  484.391833.812
   521.8 1837.53   568.3 1838.68   600.4 1842.06   660.5  1841.2   678.9 1842.61
   686.2 1844.69   707.6 1854.44   736.2 1871.95   746.9 1879.73   761.3 1895.64
   793.3 1921.66   821.9 1938.47   843.3 1955.12   898.9 1982.98   916.4 1988.72
#Mann= 5 ,-1 , 0
       0      .1       0  179.22     .06       0  298.59      .1       0
  346.93    .045       0  484.39      .1       0
Bank Sta=346.93,484.39
XS Rating Curve= 0 ,0
Exp/Cntr=0.3,0.1

Type RM Length L Ch R = 1 ,8737    ,863,782.6,668
XS GIS Cut Line= 3
2167446.93077711 328701.490418072166686.42343744329031.700905154
2166612.97114688329126.824420646
#Sta/Elev= 30
       0 2033.92    58.2 1999.39   126.1 1963.28   176.2 1938.42   247.8 1905.65
   293.3 1888.66   328.9 1873.02   337.2 1868.42   347.9 1860.69   366.3 1842.81
   378.7 1835.81   390.8 1830.23     398 1828.34   433.7 1828.19   473.1 1828.84
   498.1 1831.51   526.7 1836.55   558.9 1840.77   600.7 1840.61   626.9 1838.88
   700.5 1837.83   741.3 1834.61   773.5 1835.84   790.2 1841.25   812.9 1851.28
   829.1 1859.53   881.5 1896.26   903.5 1909.12   923.6 1918.06   949.3 1926.89
#Mann= 6 ,-1 , 0
       0      .1       0  266.38     .06       0  347.37      .1       0
   390.8    .045       0   498.1      .1       0  605.21      .1       0
Bank Sta=390.8,498.1
XS Rating Curve= 0 ,0
Exp/Cntr=0.3,0.1

Type RM Length L Ch R = 1 ,7955    ,763.8,759.4,755.7
XS GIS Cut Line= 3
2166279.63782406328255.9908604772166631.72110939 329014.32431756
2166585.88786772329130.991078973
#Sta/Elev= 30
       0 1959.12     9.7  1951.4    27.4 1932.06      64 1904.46    91.8 1881.41
   135.2 1853.18   146.1 1848.42   159.9 1836.62   182.3  1826.6   229.5 1825.59
   247.4 1827.97   261.6 1827.33   312.5 1830.64   370.4    1829   402.4 1823.93
   449.4 1825.87     468  1823.9  488.531824.444   554.8 1821.39     591  1821.6
  609.851824.799     638 1829.87   652.5 1834.28   745.8 1832.45   771.9 1835.62
   811.7 1850.56   836.1 1862.44   879.2 1894.08   912.1 1911.99   961.4 1928.89
#Mann= 6 ,-1 , 0
       0      .1       0   79.43     .06       0  203.48      .1       0
  484.74      .1       0  488.53    .045       0  609.85      .1       0
Bank Sta=488.53,609.85
XS Rating Curve= 0 ,0
Exp/Cntr=0.3,0.1

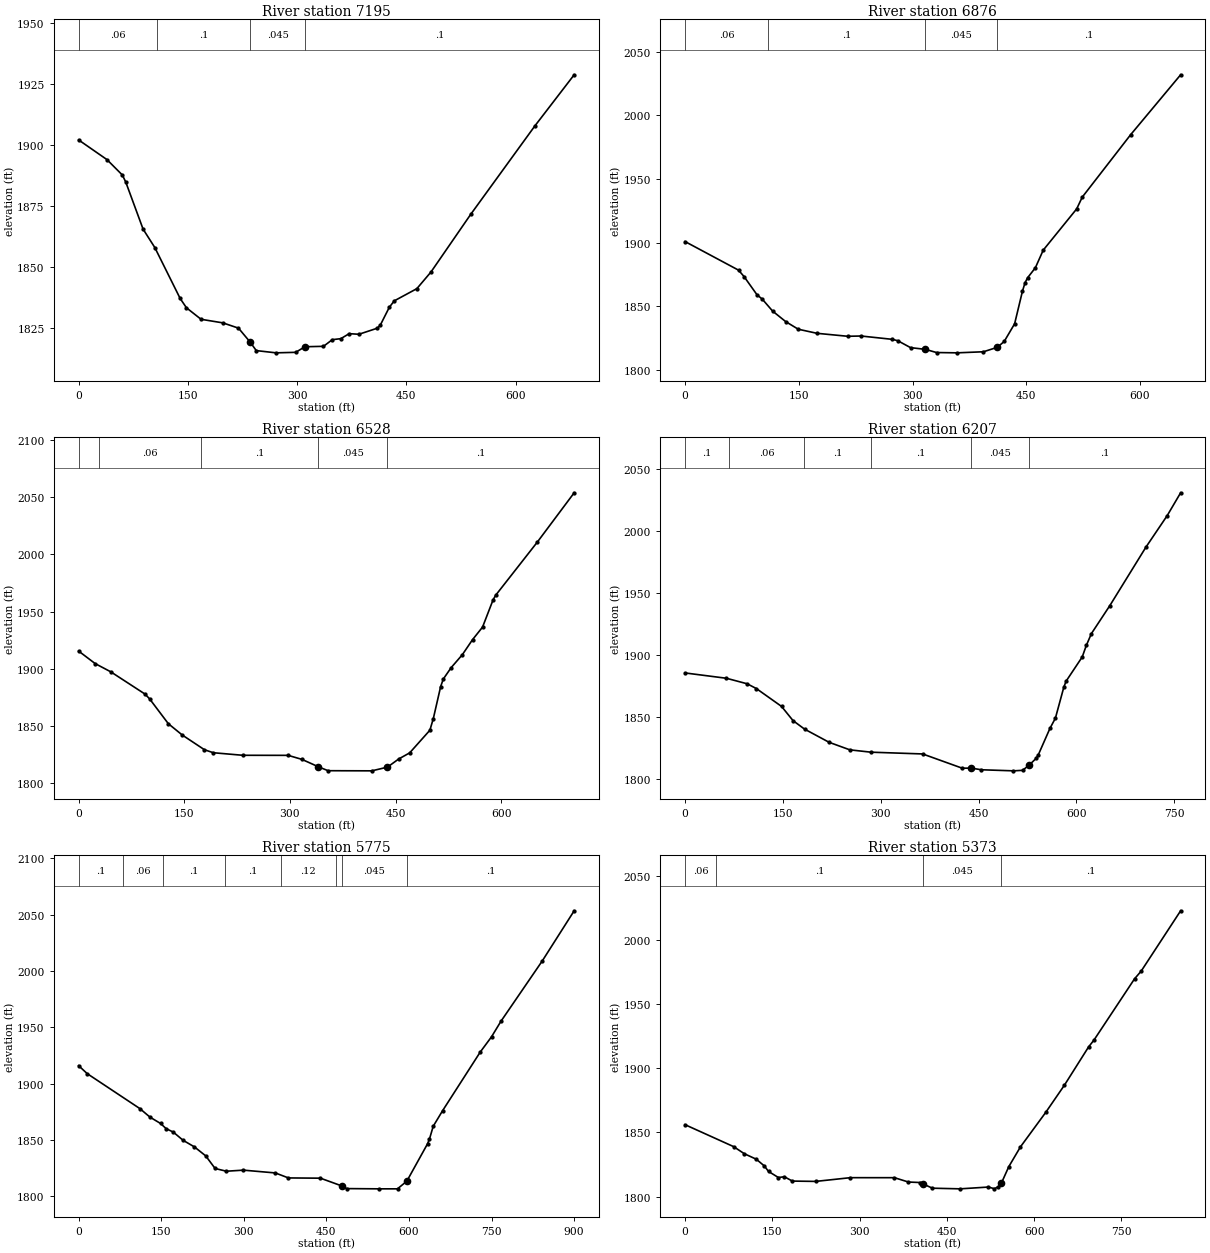
Type RM Length L Ch R = 1 ,7195    ,282.3,319.5,358.4
XS GIS Cut Line= 2
2165683.80437006328847.6576561482166044.22097206329424.741147637
#Sta/Elev= 30
       0 1902.17    38.9 1894.11      60  1887.8    64.7 1884.92    88.5 1865.61
   104.6 1858.07   139.4 1837.19   148.1 1833.36   168.1 1828.66   198.1 1827.19
   219.5 1825.03  235.52 1819.31   243.9 1815.83     271 1814.91     298 1815.12
  310.751817.407   336.2 1817.58   348.3 1820.31     360 1820.72   371.5 1822.77
   384.8 1822.52   410.2 1825.02   414.1  1826.2   426.6  1833.6   433.4 1836.22
   464.4 1841.22   483.8 1848.05   538.5 1871.74   626.6 1907.98   680.4 1928.88
#Mann= 4 ,-1 , 0
       0     .06       0  108.01      .1       0  235.52    .045       0
  310.75      .1       0
Bank Sta=235.52,310.75
XS Rating Curve= 0 ,0
Exp/Cntr=0.3,0.1

Type RM Length L Ch R = 1 ,6876    ,310.7,347.5,385.6
XS GIS Cut Line= 2
2165642.13778672328822.657706141 2165450.4711753329447.657768473
#Sta/Elev= 30
       0 1900.88    70.5 1878.43    77.8 1873.37    94.9 1859.05   101.8 1855.67
   115.5 1846.24   132.7 1838.01   149.3 1832.02   173.9 1828.82   214.5 1826.48
   232.2 1826.69   273.4 1824.07   280.6 1822.99   297.4 1817.56  317.061816.198
   331.7 1813.71   358.8 1813.47   393.5 1814.31  411.85  1817.8     421 1822.44
   434.7 1836.31     445 1861.84   448.4 1868.48   451.8 1872.45   462.1 1880.34
   472.4 1894.13   516.6  1926.6   523.9  1935.8   587.8 1984.89   653.7 2031.93
#Mann= 4 ,-1 , 0
       0     .06       0  109.35      .1       0  317.06    .045       0
  411.85      .1       0
Bank Sta=317.06,411.85
XS Rating Curve= 0 ,0
Exp/Cntr=0.3,0.1

Type RM Length L Ch R = 1 ,6528    ,317.2,321.6,327.5
XS GIS Cut Line= 2
2165635.88779922328764.3244894742165015.05439521329095.574483141
#Sta/Elev= 30
       0 1915.55    23.5 1904.61    45.6 1897.45    94.2 1878.02   100.7 1873.88
   127.4 1852.12   147.2 1842.23   178.7 1829.39   191.3 1826.78   233.1 1824.55
   297.5 1824.49   317.1 1820.98  340.381814.535   354.2 1811.09   416.4 1810.97
  438.571814.218   454.6 1821.35   470.1 1826.66   498.8 1846.43   503.7 1856.66
   514.1 1884.57   517.9 1891.18     529 1901.08   544.9 1912.39   559.4 1925.54
   573.6 1936.48   588.5 1960.22   592.2 1964.27   651.6  2010.9   703.7 2053.77
#Mann= 5 ,-1 , 0
       0      .1       0    29.2     .06       0   173.6      .1       0
  340.38    .045       0  438.57      .1       0
Bank Sta=340.38,438.57
XS Rating Curve= 0 ,0
Exp/Cntr=0.3,0.1

Type RM Length L Ch R = 1 ,6207    ,428.4,431.8,437.6
XS GIS Cut Line= 2
2165585.88757114328491.4077124742164877.55434214328766.407818645
#Sta/Elev= 30
       0 1885.69    63.4 1881.39    95.1 1876.95   109.2 1873.11   147.9 1858.66
   165.5 1847.19   183.1 1840.36   220.8 1829.69   252.6  1823.6   285.1 1821.71
   364.2 1820.29     425 1808.77  438.871808.855   454.1 1807.52   503.4 1806.65
   517.4 1807.06   527.31811.145   538.5 1816.86   541.7 1819.74   559.4 1840.91
   567.8  1849.2   580.8 1874.42   584.3 1879.14   608.9 1898.59   615.2 1907.91
     623 1917.48   651.2 1940.02   706.4 1987.12   739.2 2012.72   759.8 2031.16
#Mann= 6 ,-1 , 0
       0      .1       0   67.25     .06       0  182.74      .1       0
  284.29      .1       0  438.87    .045       0   527.3      .1       0
Bank Sta=438.87,527.3
XS Rating Curve= 0 ,0
Exp/Cntr=0.3,0.1

Type RM Length L Ch R = 1 ,5775    ,405.9,401.6,401.2
XS GIS Cut Line= 2
2165508.89494538328108.3910984952164644.44753091328359.252112789
#Sta/Elev= 30
       0 1916.01    15.6 1908.93   111.2 1877.92   129.6 1870.33   148.8 1864.71
     159  1860.1   171.9 1857.07   189.8 1849.75   210.3 1843.92   230.8 1835.97
   247.9 1824.75   268.4 1822.33   299.3 1823.28   357.2 1820.81   381.1 1816.37
   439.2 1816.15  478.281809.228     487 1806.91   545.1 1806.69   579.2 1806.69
  596.22 1813.57   633.9 1846.79   637.3 1850.97   644.1 1862.27   661.2 1876.13
   729.5 1928.11     750 1941.65   767.1 1955.42   842.3 2009.09   900.1 2053.49
#Mann= 8 ,-1 , 0
       0      .1       0   81.49     .06       0  152.36      .1       0
  265.87      .1       0  366.82     .12       0  467.77      .1       0
  478.28    .045       0  596.22      .1       0
Bank Sta=478.28,596.22
XS Rating Curve= 0 ,0
Exp/Cntr=0.3,0.1

Type RM Length L Ch R = 1 ,5373    ,417.6,420.9,424.3
XS GIS Cut Line= 2
2165371.30433889327718.4909512252164558.80432346327974.741094887
#Sta/Elev= 30
       0 1856.06    83.3 1838.99   101.9 1833.41   122.4 1829.14   136.3 1823.87
   143.4 1819.62   160.4 1814.86   170.7 1815.46   184.4 1812.08   224.5 1811.83
   284.2 1814.74   359.9 1814.73     384 1811.34   404.6 1810.95  409.591809.746
   425.3 1806.53   472.9 1806.03   521.6 1807.43   531.9 1806.11   538.8 1807.78
  543.941810.607   556.6 1823.39   576.6 1838.79   620.1 1865.71   652.3 1886.99
   693.6 1916.67   703.1 1922.18   772.7 1969.86   784.2 1975.94     852 2022.98
#Mann= 4 ,-1 , 0
       0     .06       0   52.95      .1       0  409.59    .045       0
  543.94      .1       0
Bank Sta=409.59,543.94
XS Rating Curve= 0 ,0
Exp/Cntr=0.3,0.1

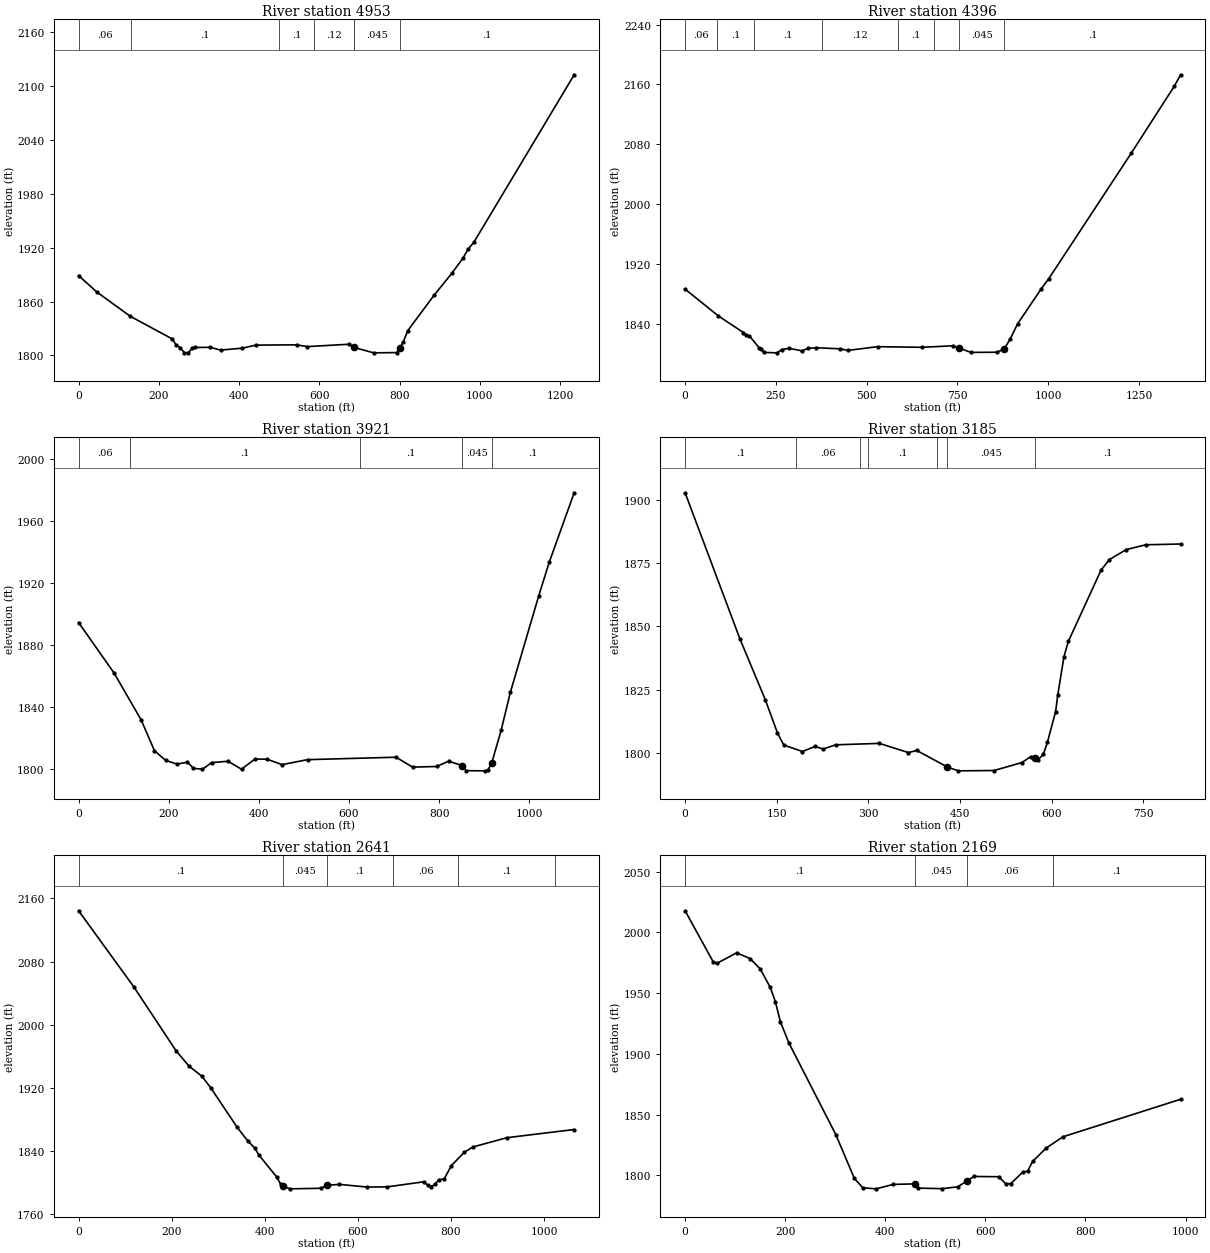
Type RM Length L Ch R = 1 ,4953    ,550.4,557.1,564.5
XS GIS Cut Line= 4
2165528.59571868327294.2599202282165379.44552365327321.771081759
2164417.31566963327549.5319100342164324.61087133327568.173986201
#Sta/Elev= 30
       0 1888.78    45.2  1870.6   128.6 1843.61   232.9 1818.48     243 1811.67
   253.2 1808.64   263.3 1803.11   273.4 1803.13   283.5 1808.23   290.2  1808.9
   327.3 1809.09   354.3 1805.98   408.2 1808.18   441.9 1811.54   543.1 1811.82
   570.1 1809.89   674.6 1812.52     686 1809.02   686.6  1808.9   735.3 1802.94
   792.6 1803.21   800.8 1808.65   809.3  1815.4   820.2 1827.65   885.6 1866.87
   930.8 1891.79   957.8 1908.28   971.3 1918.64   984.8 1925.78  1234.9 2112.08
#Mann= 7 ,-1 , 0
       0     .06       0   130.4      .1       0  499.16      .1       0
  587.02     .12       0     686    .045       0   686.6    .045       0
   800.8      .1       0
Bank Sta=686.6,800.8
XS Rating Curve= 0 ,0
Exp/Cntr=0.3,0.1

Type RM Length L Ch R = 1 ,4396    ,467.8,474.9,486.5
XS GIS Cut Line= 2
2165489.87332265326834.8845543592164131.72118814326970.574468061
#Sta/Elev= 30
       0 1885.99    91.5 1850.21   160.8 1827.89   167.4 1824.38   177.2 1823.47
   203.6 1807.78   210.2  1806.3   216.8 1801.35   253.1  1800.8   266.3 1805.15
     286 1806.86   322.3 1803.46   337.8 1806.73   361.9 1807.62   427.8 1806.14
   447.7    1804     530 1809.05     652 1808.19   737.8 1810.26   754.2 1807.33
   787.2 1801.38   859.8 1801.63   879.5 1806.36     896 1819.91   915.8 1839.52
   981.1 1886.59  1001.5 1899.87    1229 2067.99  1347.7 2157.73  1364.9 2172.77
#Mann= 8 ,-1 , 0
       0     .06       0   89.21      .1       0  188.77      .1       0
  376.61     .12       0  587.01      .1       0  686.57      .1       0
   754.2    .045       0   879.5      .1       0
Bank Sta=754.2,879.5
XS Rating Curve= 0 ,0
Exp/Cntr=0.3,0.1

Type RM Length L Ch R = 1 ,3921    ,747.9,735.5,711.6
XS GIS Cut Line= 2
2165508.80439197326597.6575629712164425.47092871326408.074280724
#Sta/Elev= 30
       0 1894.25    78.5 1861.84   138.8 1831.51   168.3 1811.67   193.2 1805.44
   218.2  1803.1   241.6 1804.28   254.9 1800.34   274.9 1799.74   294.9    1804
   331.5  1804.9   361.5 1799.78   391.4 1806.33   418.1 1806.22   451.4 1802.71
     508 1805.93   704.5  1807.5   741.2 1801.11   794.5 1801.52   821.1 1804.94
     8511802.128   860.8 1798.82     901 1798.72   907.7 1798.99   916.5 1803.49
   937.7 1824.85   958.3 1849.46  1020.9 1911.26  1044.3 1933.06  1099.8 1977.92
#Mann= 5 ,-1 , 0
       0     .06       0  114.28      .1       0  623.93      .1       0
     851    .045       0   916.5      .1       0
Bank Sta=851,916.5
XS Rating Curve= 0 ,0
Exp/Cntr=0.3,0.1

Type RM Length L Ch R = 1 ,3185    ,573.8,544.6,487.3
XS GIS Cut Line= 4
2165577.45834802326038.532036758 2165208.8043358325937.240904808
2164979.63779938 325876.824358972164793.39154182 325831.26034654
#Sta/Elev= 30
       0 1902.69      90 1844.83   131.3 1820.96   151.2 1807.84   161.5 1803.07
   192.1 1800.51   212.5  1802.5   226.1 1801.51   246.5 1803.16     318 1803.72
   365.6 1800.09   379.2 1800.92  429.091794.413   447.1 1792.88   505.7 1793.01
   551.3 1796.15   565.8 1798.51  571.931798.117   578.2 1797.32   586.4 1799.43
     593 1804.12   606.5  1816.3   609.9  1822.7   620.1 1837.96   627.3    1844
   680.8 1872.13   694.4 1876.31     722 1880.25   754.1 1882.15   811.1 1882.46
#Mann= 7 ,-1 , 0
       0      .1       0  181.97     .06       0   285.6      .1       0
  299.96      .1       0   411.9      .1       0  429.09    .045       0
  571.93      .1       0
Bank Sta=429.09,571.93
XS Rating Curve= 0 ,0
Exp/Cntr=0.3,0.1

Type RM Length L Ch R = 1 ,2641    ,498,472,422.2
XS GIS Cut Line= 2
2165585.88757114325143.4908518942164700.47103488325735.157647565
#Sta/Elev= 30
       0 2144.35   118.6 2047.99   209.2 1967.27   236.8 1947.94   265.2 1934.69
   284.1 1920.06   340.8 1870.13   363.1 1853.19   378.9 1843.79   386.8 1835.54
     426 1807.09   434.1    1798  439.071795.828   454.4 1792.31   520.1 1793.03
  534.091796.712   560.4 1797.95   619.6 1794.59     663 1794.78   741.9 1801.24
   750.4 1796.59   757.7 1795.17   765.6 1797.88   773.5 1803.62   785.5 1804.76
   801.1 1821.79   828.7 1838.48     847 1845.28   920.4 1857.08  1064.9  1867.4
#Mann= 6 ,-1 , 0
       0      .1       0  439.07    .045       0  534.09      .1       0
  676.54     .06       0   815.7      .1       0 1024.25      .1       0
Bank Sta=439.07,534.09
XS Rating Curve= 0 ,0
Exp/Cntr=0.3,0.1

Type RM Length L Ch R = 1 ,2169    ,453,413.9,394.7
XS GIS Cut Line= 2
2164887.97098798324741.4076665642164673.38775572325708.074368387
#Sta/Elev= 30
       0 2017.81    55.9 1975.94    63.1 1974.42     103 1983.19   129.8 1978.47
     150 1969.98   170.2 1954.71   180.3 1943.08   190.3  1926.6   207.1 1909.22
   301.2 1833.49   338.2 1797.46     355 1789.72   381.9 1788.85   415.5 1792.49
  459.031792.945   465.9 1789.44     513 1789.01   544.4 1790.48  563.95 1795.47
   576.8 1799.04   626.9 1798.81   640.7 1792.96   650.7 1793.14   674.3 1802.44
   684.4 1803.47   694.4 1811.37   721.3 1822.35   754.9 1831.69   990.2 1862.61
#Mann= 4 ,-1 , 0
       0      .1       0  459.03    .045       0  563.95     .06       0
  736.03      .1       0
Bank Sta=459.03,563.95
XS Rating Curve= 0 ,0
Exp/Cntr=0.3,0.1

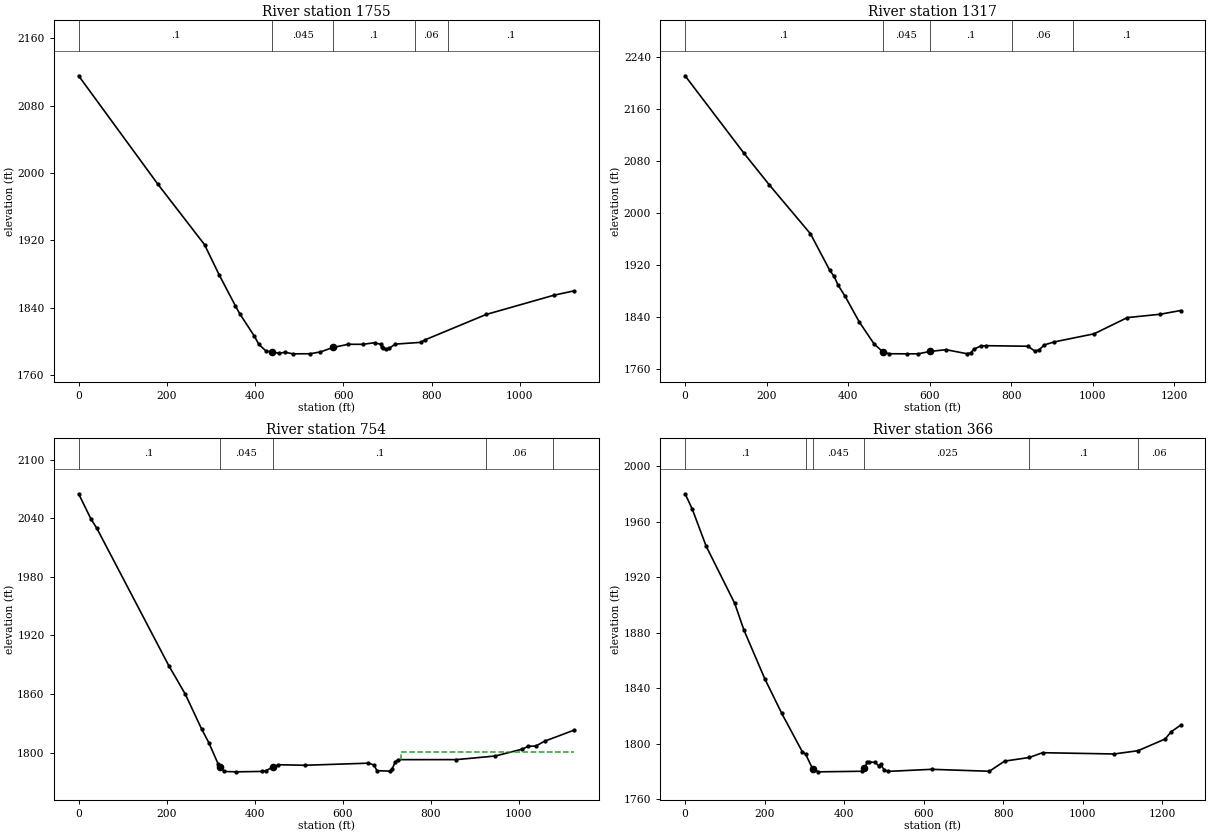
Type RM Length L Ch R = 1 ,1755    ,445.8,438.2,433.2
XS GIS Cut Line= 2
2164308.51332021324622.5616695222164487.60566804325731.182802138
#Sta/Elev= 30
       0 2115.59     179 1987.13   285.3 1914.91   318.1 1879.41   355.1 1842.35
   365.1 1832.78   398.5 1805.93   408.3 1796.41   424.9 1788.39  438.911787.178
   454.8 1785.88   468.1 1786.98   485.7 1785.13   524.6 1785.24   547.9 1787.41
  576.481792.708     611 1796.46   644.3 1796.47   670.9 1798.34   684.1 1796.52
   687.5 1793.11   690.8 1791.68   697.4 1790.98   704.1 1791.84   717.4  1796.7
   775.9 1798.79   784.5 1801.64   923.4 1831.89  1076.3 1854.69    1123 1860.03
#Mann= 5 ,-1 , 0
       0      .1       0  438.91    .045       0  576.48      .1       0
  761.45     .06       0  836.93      .1       0
Bank Sta=438.91,576.48
XS Rating Curve= 0 ,0
Exp/Cntr=0.3,0.1

Type RM Length L Ch R = 1 ,1317    ,562.5,562,561.1
XS GIS Cut Line= 2
2163819.22115697324672.6578040572164129.63785897325847.657750636
#Sta/Elev= 30
       0 2211.01   144.5 2091.67   206.8 2042.82   307.4 1967.79   354.9 1911.41
   365.6 1902.02   375.3 1888.58   392.2 1871.76   426.9 1832.31   463.5 1798.13
  484.811786.056   500.8 1783.06     545 1782.91   572.1 1782.97  599.471786.516
     640  1789.3   690.9 1783.14   700.7 1784.59   707.8 1789.87   724.8 1794.98
   738.3 1795.47   840.8 1794.61   857.1 1787.38   867.3 1788.64   880.9 1796.61
   904.6 1801.15  1003.1 1813.76  1084.5  1838.7  1165.1 1843.87  1215.3 1849.62
#Mann= 5 ,-1 , 0
       0      .1       0  484.81    .045       0  599.47      .1       0
  801.55     .06       0  951.02      .1       0
Bank Sta=484.81,599.47
XS Rating Curve= 0 ,0
Exp/Cntr=0.3,0.1

Type RM Length L Ch R = 1 ,754     ,399.7,388.6,385.7
XS GIS Cut Line= 2
2163312.97118522324972.6575321412163612.97091331326058.074324563
#Sta/Elev= 30
       0 2064.92    27.7 2039.37    41.4 2029.55   204.7 1889.18   242.5 1859.77
   279.3 1824.32   295.8 1810.24   317.1 1788.38  320.811785.788   330.7 1780.74
   357.9 1780.36   415.8 1780.78     426 1781.62  441.931785.386   453.2 1787.63
   514.5 1787.09   658.5 1789.23   671.1 1787.37   677.9 1781.54   708.5 1781.08
   711.9 1782.99   719.8 1790.55   725.5 1792.83   858.5 1792.87   946.8 1796.57
  1008.5 1803.63  1021.7 1806.55  1038.7 1806.72  1059.1 1811.76  1126.1 1823.05
#Mann= 5 ,-1 , 0
       0      .1       0  320.81    .045       0  441.93      .1       0
   925.6     .06       0 1077.54      .1       0
#XS Ineff= 2 , 0
                          733.45         1800.57
Permanent Ineff=
       F       F
Bank Sta=320.81,441.93
XS Rating Curve= 0 ,0
Exp/Cntr=0.3,0.1

Type RM Length L Ch R = 1 ,366     ,369,365,334
XS GIS Cut Line= 4
2162888.40498979325051.6481815552163057.76913694325486.433753366
2163366.16355416325812.5229322242163553.22246296326085.527826152
#Sta/Elev= 30
       0 1980.21    17.9 1969.27    53.1 1942.37   124.8 1901.27   148.1 1881.93
   200.4 1846.96   243.2 1821.93   294.6 1794.45   303.1 1792.61   320.7 1782.09
   335.1 1779.87   443.9 1780.28   450.9  1782.4     458 1786.72   461.8    1787
   478.1 1786.69   487.7 1784.03   491.7 1785.26   500.7 1781.28   509.7 1780.18
     620 1781.69   765.3 1780.28   803.5 1787.59     866 1790.22     899 1793.66
  1079.1 1792.74  1139.2  1795.1  1207.4 1803.53  1222.3 1808.68  1246.4 1813.49
#Mann= 6 ,-1 , 0
       0      .1       0   303.1    .025       0   320.7    .045       0
   450.9    .025       0     866      .1       0  1139.2     .06       0
Bank Sta=320.7,450.9
XS Rating Curve= 0 ,0
Exp/Cntr(USF)=0,0
Exp/Cntr=0.3,0.1
LCMann Table=0

Chan Stop Cuts=-1
Use User Specified Reach Order=0
Composite Channel Slope=5